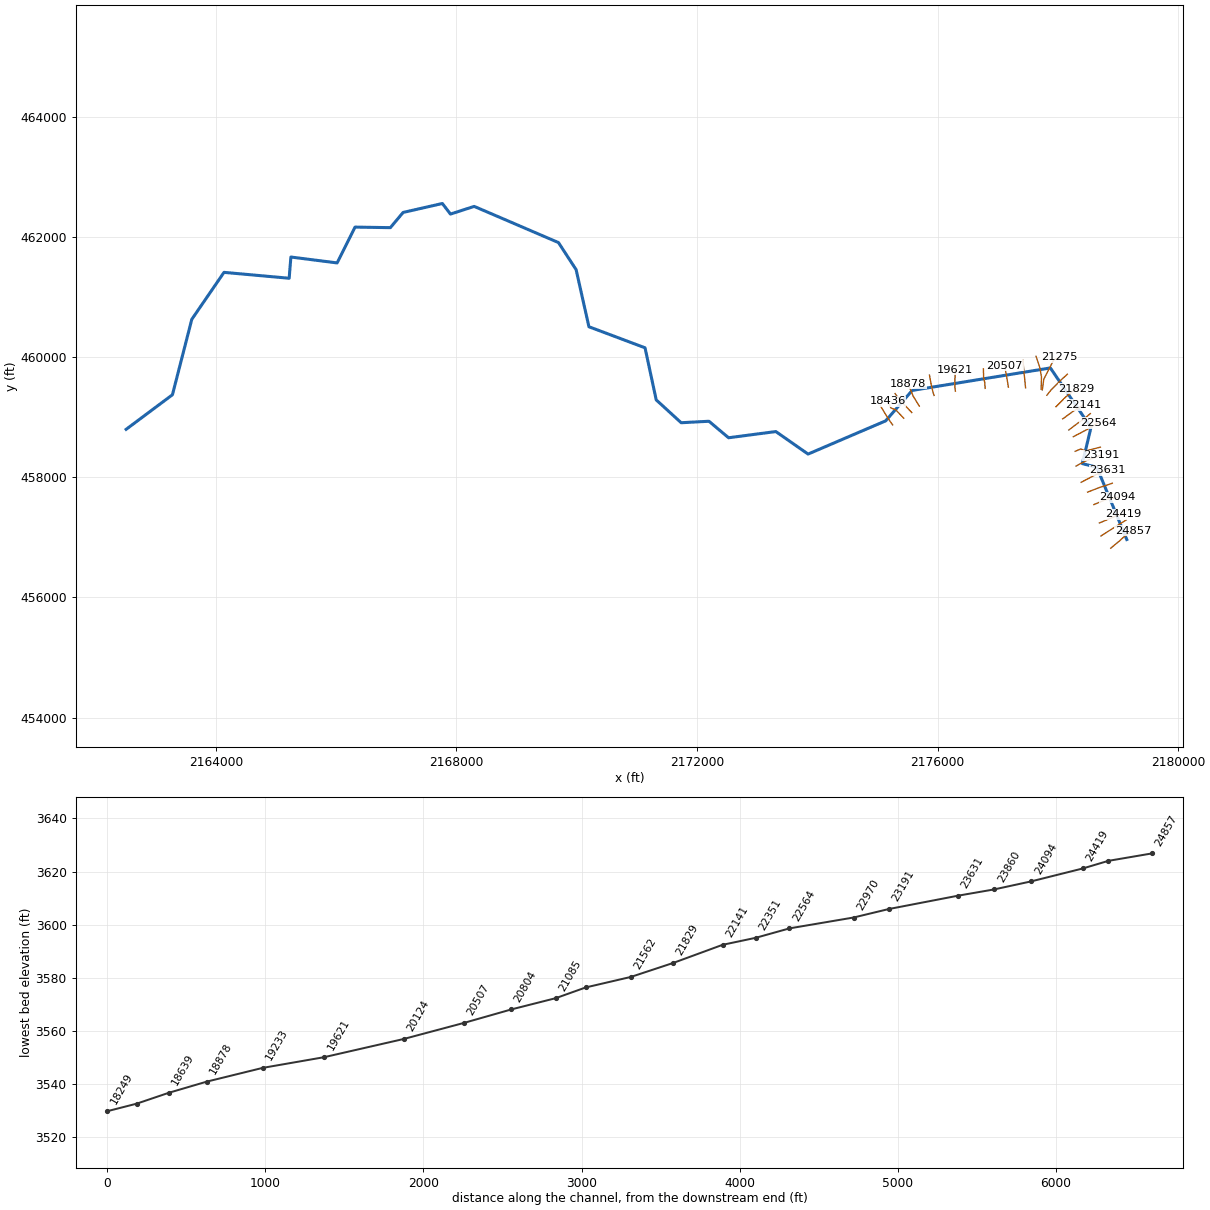
--- NFCRNBRYRV.prj (project) ---

Proj Title=NFCRNBRYRV
Current Plan=p01
Default Exp/Contr=0,0
English Units
Geom File=g01
Flow File=f01
Plan File=p01
Background Map Layer=Inundation Boundary (01pct Value_0)
BEGIN DESCRIPTION:
----------MODEL BY WOOD PLC 2021----------
Stream Name: North Fork Cranberry River
Flood Zone: Approximate
Pocahontas County, WV
HEC-RAS Version: RAS 6.1
Vertical Datum: NAVD88
Projection: NAD 1983 StatePlane West Virginia S FIPS 4702 (US Feet)
Terrain: 1-meter LIDAR (FEMA Region III 3DEP collected 2016-2018)
Land Use: 2019 NLCD
Hydrologic Method:
Gage-Weighted WV 2010 RRE
END DESCRIPTION:
DSS Export Rating Curves= 0
DSS Export Rating Curve Sorted= 0
DSS Export Volume Flow Curves= 0
DXF Filename=.\Backup\f00_befKM\NFCRNBRYRV.
DXF OffsetX= 0
DXF OffsetY= 0
DXF ScaleX= 0
DXF ScaleY= 0

--- NFCRNBRYRV.p01 (plan) ---

Plan Title=Floodplain
Program Version=6.10
Short Identifier=Floodplain
Geom File=g01
Flow File=f01
Subcritical Flow
K Sum by GR= 0
Std Step Tol= 0.01
Critical Tol= 0.01
Num of Std Step Trials= 20
Max Error Tol= 0.3
Flow Tol Ratio= 0.001
Split Flow NTrial= 30
Split Flow Tol= 0.02
Split Flow Ratio= 0.02
Log Output Level= 0
Friction Slope Method= 1
Unsteady Friction Slope Method= 2
Unsteady Bridges Friction Slope Method= 1
Parabolic Critical Depth
Global Vel Dist= 0 , 0 , 0
Global Log Level= 0
CheckData=True
Encroach Param=-1 ,0,0, 0
Mapping Interval=1HOUR
Computation Time Step Use Courant=        0
Computation Time Step Use Time Series=    0
Computation Time Step Count To Double=0
Computation Time Step Max Doubling=0
Computation Time Step Max Halving=0
Computation Time Step Residence Courant=0
Run HTab= 0
Run UNet= 0
Run Sediment= 0
Run PostProcess= 0
Run WQNet= 0
Run RASMapper=-1
UNET Theta= 0
UNET Theta Warmup= 0
UNET ZTol= 0
UNET ZSATol= 0
UNET MxIter= 0
UNET Max Iter WO Improvement= 0
UNET MaxInSteps= 0
UNET DtIC= 0
UNET DtMin= 0
UNET MaxCRTS= 0
UNET WFStab= 0
UNET SFStab= 0
UNET WFX= 1
UNET SFX= 1
UNET Gravity=32.174
UNET 1D Methodology=Finite Difference
UNET DSS MLevel= 1
UNET Pardiso=0
UNET DZMax Abort= 0
UNET Use Existing IB Tables= 0
UNET Froude Reduction=False
UNET Froude Limit= 0
UNET Froude Power= 0
UNET D1 Cores= 0
UNET WindReference=Eulerian
UNET WindDragFormulation=Hsu (1988)
UNET D2 Coriolis=0
UNET D2 Cores= 0
UNET D2 Theta= 1
UNET D2 Theta Warmup= 1
UNET D2 Z Tol= 0.01
UNET D2 Volume Tol= 0.01
UNET D2 Max Iterations= 20
UNET D2 Equation= 0
UNET D2 RampUpFraction=0.1
UNET D2 TimeSlices= 1
UNET D2 Turbulence Formulation=Non-Conservative (original)
UNET D2 Eddy Viscosity=0.3
UNET D2 Transverse Eddy Viscosity=0.1
UNET D2 Smagorinsky Mixing=0
UNET D2 BCVolumeCheck=0
UNET D2 Cores=0
UNET D2 SolverType=PARDISO (Direct)
UNET D2 Minimum Iterations= 2147483647
UNET D2 Maximum Iterations= 2147483647
UNET D2 Restart Number= 10
UNET D2 Relaxation Coeff=1.3
UNET D2 SOR Precondition Iterations= 10
UNET D2 ILUT Maximum Fill= 8
UNET D2 ILUT Tolerance=1E-08
UNET D1D2 MaxIter= 0
UNET D1D2 ZTol=0.01
UNET D1D2 QTol=0.1
UNET D1D2 MinQTol=1
Write IC File= 0
Write IC File at Fixed DateTime=0
Write IC File at Sim End=0
Echo Input=False
Echo Parameters=False
Echo Output=False
Write Detailed= 0
HDF Write Warmup=0
HDF Write Time Slices=0
HDF Flush=0
HDF Compression= 1
HDF Chunk Size= 1
HDF Spatial Parts= 1
HDF Use Max Rows=0
HDF Fixed Rows= 1
Calibration Method= 0
Calibration Iterations= 20
Calibration Max Change=0.05
Calibration Tolerance=0.2
Calibration Maximum=1.5
Calibration Minimum=0.5
Calibration Optimization Method= 1
WQ AD Non Conservative
WQ ULTIMATE=-1
WQ Max Comp Step=1HOUR
WQ Output Interval=15MIN
WQ Output Selected Increments= 0
WQ Output face flow=0
WQ Output face velocity=0
WQ Output face area=0
WQ Output face dispersion=0
WQ Output cell volume=0
WQ Output cell surface area=0
WQ Output cell continuity=0
WQ Output cumulative cell continuity=0
WQ Output face conc=0
WQ Output face dconc_dx=0
WQ Output face courant=0
WQ Output face peclet=0
WQ Output face adv mass=0
WQ Output face disp mass=0
WQ Output cell mass=0
WQ Output cell source sink temp=0
WQ Output nsm pathways=0
WQ Output nsm derived pathways=0
WQ Create Restart=0
WQ Fixed Restart=0
WQ System Summary=0
WQ Write To DSS=0
Sorting and Armoring Iterations= 10
XS Update Threshold= 0.02
Bed Roughness Predictor= 0
Hydraulics Update Threshold= 0.02
Energy Slope Method= 1
Volume Change Method= 1
Sediment Retention Method= 0
Sediment TS Multiplier= 1
Warm Up Method= 0
XS Weighting Method= 0
Number of US Weighted Cross Sections= 1
Number of DS Weighted Cross Sections= 1
Upstream XS Weight=0
Main XS Weight=1
Downstream XS Weight=0
Number of DS XS's Weighted with US Boundary= 1
Upstream Boundary Weight= 1
Weight of XSs Associated with US Boundary= 0
Number of US XS's Weighted with DS Boundary= 1
Downstream Boundary Weight= 0.5
Weight of XSs Associated with DS Boundary= 0.5
Percentile Method= 0
Sediment Output Level= 3
Mass or Volume Output= 0
Output Increment Type= 1
Profile and TS Output Increment= 1
Transport Output Increment 1
XS Output Flag= 0
XS Output Increment= 10
Read HDF5 Sediment Hotstart= 0
Sediment Hotstart Type= 0
Write Gradation File= 0
Read Gradation Hotstart= 0
Write HDF5 File= 1
Write Binary Output= 1
Write DSS Sediment File= 0
DSS Sediment Output Type= 1
SV Curve= 0
Specific Gage Flag= 0
Subcell Erosion Methods= 0
Subcell Deposition Methods= 0
Advection Scheme= 1
Matrix Solver= 0
Implicit Weighting Factor= 1
Maximum Outer Loop Convergence Iterations= 5
Convergence Maximum Absolute= 0.001
Convergence RMSE= 0.0001
Grain Fractions Max Abs Error= 0.001
Max Subgrid Regions= 1
Max Subgrid Length Scale= 3.402823E+38
Initial Layer Thickness= 3.402823E+38
Min Layer Thickness= 3.402823E+38
Max Layer Thickness= 3.402823E+38
Number of Layers= 5

--- NFCRNBRYRV.f01 (steady flow) ---

Flow Title=Flow
Program Version=6.10
Number of Profiles= 6
Profile Names=01pct,10pct,04pct,02pct,0_2pct,01plus
River Rch & RM=NFCRNBRYRV,Main            ,24857
     609     322     428     516     849     900
River Rch & RM=NFCRNBRYRV,Main            ,23860
     683     363     482     579     951    1010
River Rch & RM=NFCRNBRYRV,Main            ,21275
    1700     893    1180    1430    2460    2650
River Rch & RM=NFCRNBRYRV,Main            ,19233
    1940    1020    1350    1630    2800    3030
River Rch & RM=NFCRNBRYRV,Main            ,15239
    2170    1150    1510    1830    3120    3390
River Rch & RM=NFCRNBRYRV,Main            ,9117
    2450    1300    1710    2060    3510    3830
River Rch & RM=NFCRNBRYRV,Main            ,6740
    2810    1500    1970    2370    4020    4390
Boundary for River Rch & Prof#=NFCRNBRYRV,Main            , 1
Up Type= 0
Dn Type= 3
Dn Slope=0.01719
Boundary for River Rch & Prof#=NFCRNBRYRV,Main            , 2
Up Type= 0
Dn Type= 3
Dn Slope=0.01719
Boundary for River Rch & Prof#=NFCRNBRYRV,Main            , 3
Up Type= 0
Dn Type= 3
Dn Slope=0.01719
Boundary for River Rch & Prof#=NFCRNBRYRV,Main            , 4
Up Type= 0
Dn Type= 3
Dn Slope=0.01719
Boundary for River Rch & Prof#=NFCRNBRYRV,Main            , 5
Up Type= 0
Dn Type= 3
Dn Slope=0.01719
Boundary for River Rch & Prof#=NFCRNBRYRV,Main            , 6
Up Type= 0
Dn Type= 3
Dn Slope=0.01719
DSS Import GetInterval= 0
DSS Import GetPeak= 0
DSS Import FillOption= 0

--- NFCRNBRYRV.g01 (geometry) ---

Geom Title=Geometry
Program Version=6.10

River Reach=NFCRNBRYRV      ,Main
Reach XY= 30
2179144.36406305456963.7810165582178646.83290589458166.176905721
 2178405.9669178458226.4950265592178549.17496473458827.711999983
2177874.02408405459818.4268820582175577.77703613459444.811159477
2175135.94196181458938.1530520622173845.57183914458385.572136223
2173309.59193997458760.1491429812172523.91306514458656.817000553
2172198.02592164458931.4260313962171735.77389339458907.035988316
2171320.98404056459286.9771575632171135.10809997460153.677851975
2170202.16705248460504.0879123062169989.17502439461453.698873982
2169695.78912821461904.4929198922168294.58097264462506.378855228
2167899.97349414462378.4329168952167765.19784506462554.460123897
2167113.05708897 462405.681878152166900.67595205462152.658105984
2166313.58001339462161.7030353992166015.62391639461565.832836062
2165246.90399714461663.8841491492165218.16028821461310.850734472
2164134.88784847461408.7931239012163599.52212131460627.619161308
2163277.55098046 459372.448115232162507.73001355458797.072953641

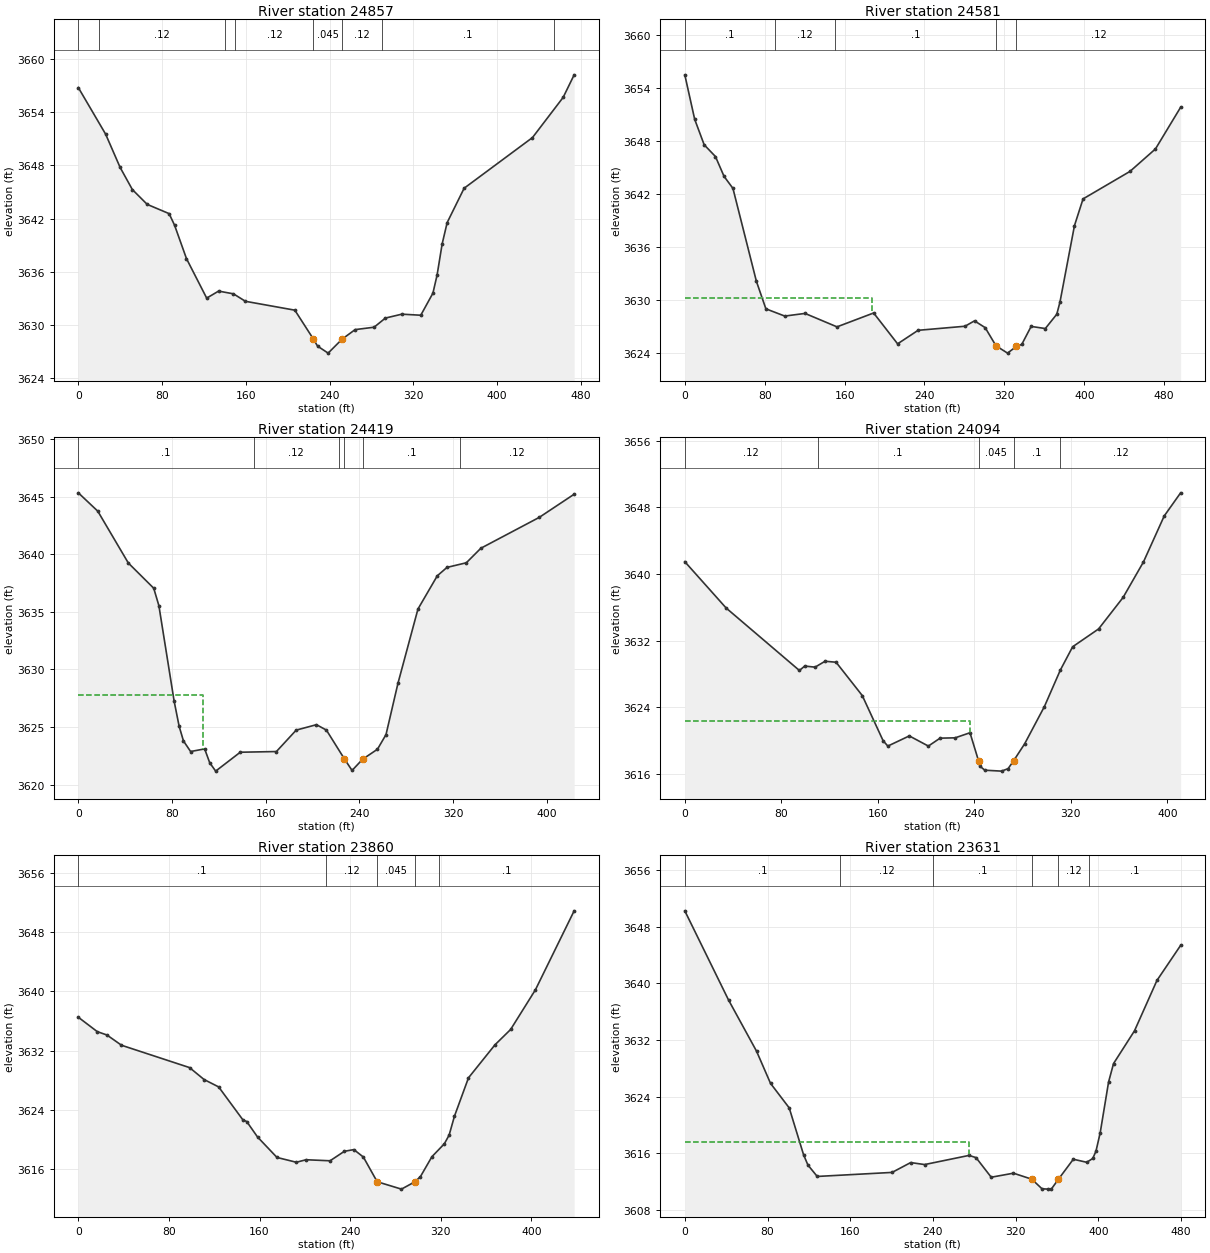
Type RM Length L Ch R = 1 ,24857   ,279.9,276.4,272.6
XS GIS Cut Line= 4
2178877.44088861456819.2254957692179023.68575044456940.454789125
2179108.35382834457017.4257690332179248.82586667457111.715219421
#Sta/Elev= 30
       0 3656.76    26.1 3651.51    39.9 3647.77    51.6 3645.27    65.8  3643.6
    86.7 3642.56    91.9 3641.26   103.3 3637.49   122.6 3633.04     134 3633.83
   148.2 3633.52   159.6 3632.68   206.8 3631.68  224.573628.418   228.5 3627.63
   238.6 3626.84  251.963628.418   264.4 3629.49   282.5 3629.76   293.3 3630.79
     309 3631.23   327.1 3631.11   338.7  3633.6   342.7 3635.65   347.5 3639.14
   352.3 3641.55   368.5 3645.42   433.8 3651.13   463.1 3655.66   473.6  3658.2
#Mann= 8 ,-1,0
       0      .1       0      20     .12       0     140      .1       0
     150     .12       0  224.57    .045       0  251.96     .12       0
  289.96      .1       0  454.38     .12       0
Bank Sta=224.57,251.96
XS Rating Curve= 0 ,0
Exp/Cntr(USF)=0,0
Exp/Cntr=0.3,0.1

Type RM Length L Ch R = 1 ,24581   ,162.6,161.3,158.4
XS GIS Cut Line= 4
2178715.80183081457023.1985925262178935.16912354457163.670630859
2179044.85276991457232.9445127772179135.29367131 457288.74847321
#Sta/Elev= 30
       0  3655.5     9.9 3650.47    19.4 3647.59    30.7 3646.26    39.3 3644.02
    48.2 3642.66    71.7 3632.15    81.2 3629.04   100.1 3628.22   120.4 3628.52
   152.4    3627   189.1 3628.57   213.1 3625.08   233.6 3626.61   280.6 3627.07
   290.1 3627.68   300.8 3626.91   311.6 3624.86   323.2 3624.03   331.9 3624.78
   337.4 3625.01   346.8 3627.05     361 3626.81   372.5 3628.43   375.7 3629.81
   390.2 3638.45   398.8 3641.47   445.8 3644.58   471.3 3647.12   496.5 3651.83
#Mann= 5 ,-1,0
       0      .1       0      90     .12       0     150      .1       0
   311.6    .045       0   331.9     .12       0
#XS Ineff= 2 , 0
          187.57  3630.3
Permanent Ineff=
       F       F
Bank Sta=311.6,331.9
XS Rating Curve= 0 ,0
Exp/Cntr(USF)=0,0
Exp/Cntr=0.3,0.1

Type RM Length L Ch R = 1 ,24419   ,326.2,325.6,322.6
XS GIS Cut Line= 4
2178688.86198784 457238.717336272178865.89524163 457313.76404168
2178952.48759402457350.3252571372179085.26253437457384.962198096
#Sta/Elev= 30
       0 3645.32    16.6 3643.73    42.7 3639.23    64.4 3637.04    68.8 3635.53
    81.8 3627.26    86.1 3625.06    89.8 3623.79    95.9 3622.87   107.9  3623.1
   112.2  3621.9   117.3 3621.17   138.3 3622.81   169.2 3622.87   186.1 3624.73
   203.4  3625.2   211.9 3624.73   227.2 3622.24   233.8 3621.23   242.8  3622.2
   255.5 3623.07   262.8 3624.34     273 3628.79   290.1 3635.24   306.6 3638.12
   314.9 3638.85   331.4 3639.25   343.8 3640.51   393.7 3643.19   423.5  3645.2
#Mann= 6 ,-1,0
       0      .1       0     150     .12       0  222.28      .1       0
   227.2    .045       0   242.8      .1       0  326.28     .12       0
#XS Ineff= 2 , 0
          106.53 3627.74
Permanent Ineff=
       F       F
Bank Sta=227.2,242.8
XS Rating Curve= 0 ,0
Exp/Cntr(USF)=0,0
Exp/Cntr=0.3,0.1

Type RM Length L Ch R = 1 ,24094   ,230.8,234,234
XS GIS Cut Line= 4
2178596.49681195457544.6769814052178785.07571272457623.572235811
 2178888.9865356457648.5878042822178987.12453498457665.906274761
#Sta/Elev= 30
       0 3641.47    34.3  3635.9      95  3628.4    99.4 3628.93     108  3628.8
   116.3 3629.51   125.4 3629.39   147.1 3625.39   164.4 3619.96   168.3 3619.32
   186.1 3620.54   201.9 3619.32   211.6 3620.27   224.1 3620.31   236.4 3620.92
  243.513617.539   244.6 3616.91   248.7 3616.42   262.6 3616.31     268 3616.61
   272.53617.539   281.7 3619.59   298.1 3624.07   311.3 3628.45   321.5 3631.25
     343 3633.39   363.3 3637.17   380.2 3641.44   397.4 3646.96     411 3649.74
#Mann= 5 ,-1,0
       0     .12       0     110      .1       0  243.51    .045       0
   272.5      .1       0   311.3     .12       0
#XS Ineff= 2 , 0
          236.52 3622.37
Permanent Ineff=
       F       F
Bank Sta=243.51,272.5
XS Rating Curve= 0 ,0
Exp/Cntr(USF)=0,0
Exp/Cntr=0.3,0.1

Type RM Length L Ch R = 1 ,23860   ,227.2,228.1,229.4
XS GIS Cut Line= 4
2178492.58598907457752.4986271582178686.93771334457827.545332568
2178823.56120268457871.8036460162178904.38073158457900.667763481
#Sta/Elev= 30
       0  3636.5    16.7 3634.56    25.3  3634.1    38.1 3632.72    98.2  3629.7
     111 3628.09   123.9 3627.09   145.3 3622.64   148.7 3622.41   158.2 3620.33
   175.4 3617.56   192.5 3616.91   201.1 3617.25   222.3 3617.11   234.9 3618.39
   243.3 3618.62   251.7 3617.61  263.873614.278   285.3 3613.28  297.243614.276
   302.1 3614.98   312.2 3617.66   323.2 3619.41   327.4 3620.58   332.1 3623.13
   344.5 3628.32   367.9 3632.78   381.7 3634.85   403.6 3640.21   437.8 3650.88
#Mann= 5 ,-1,0
       0      .1       0  218.34     .12       0  263.87    .045       0
  297.24     .12       0  318.34      .1       0
Bank Sta=263.87,297.24
XS Rating Curve= 0 ,0
Exp/Cntr(USF)=0,0
Exp/Cntr=0.3,0.1

Type RM Length L Ch R = 1 ,23631   ,418.9,440.4,435.8
XS GIS Cut Line= 4
 2178386.7508917457916.0619594632178617.66383142458037.291252818
2178763.90869325458096.9437622472178821.63692818458116.186507224
#Sta/Elev= 30
       0 3650.22    42.3 3637.63    69.4  3630.4    82.9 3625.86     101 3622.39
   114.9 3615.77   119.1 3614.32   128.1 3612.71   200.5 3613.28   218.5 3614.67
     232 3614.39   274.9 3615.68   281.7 3615.37   296.4  3612.6   317.9 3613.17
  335.653612.323   345.5 3610.97   351.6 3610.92   354.7 3610.96  361.433612.323
   375.8 3615.14   388.8 3614.71   394.6 3615.25   397.7 3616.27   401.8 3618.87
   409.9 3626.04   414.7 3628.65     435 3633.28   456.7 3640.39   479.6 3645.34
#Mann= 6 ,-1,0
       0      .1       0     150     .12       0     240      .1       0
  335.65    .045       0  361.43     .12       0   390.8      .1       0
#XS Ineff= 2 , 0
          274.48 3617.58
Permanent Ineff=
       F       F
Bank Sta=335.65,361.43
XS Rating Curve= 0 ,0
Exp/Cntr(USF)=0,0
Exp/Cntr=0.3,0.1

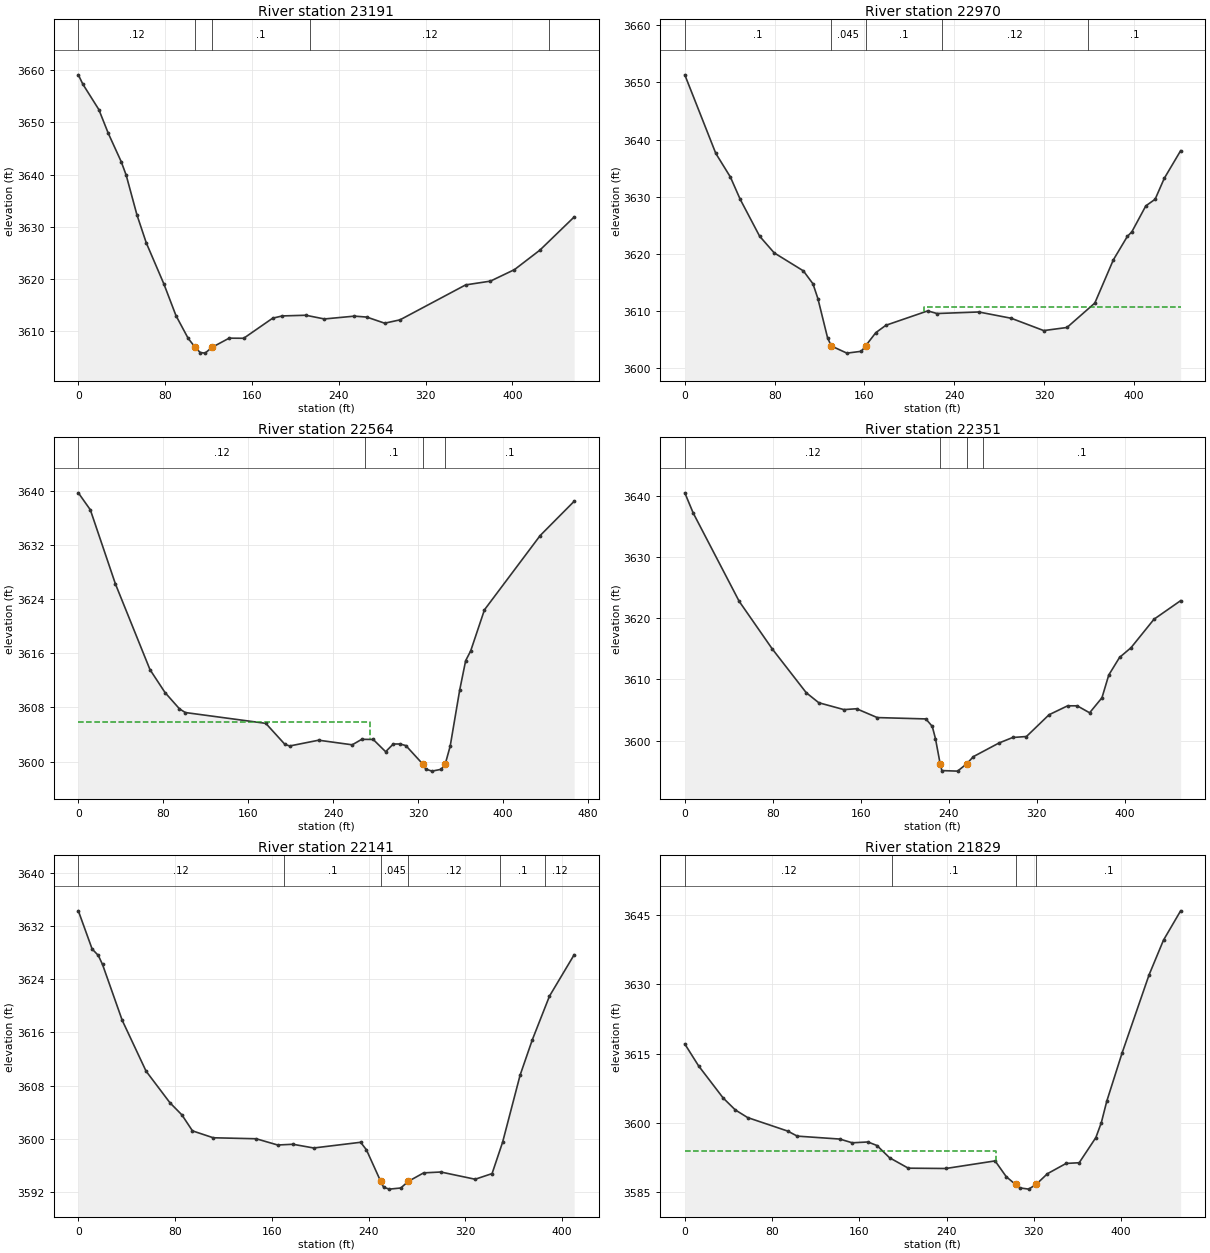
Type RM Length L Ch R = 1 ,23191   ,232.1,221.5,205.9
XS GIS Cut Line= 4
 2178302.0828138458185.4603891422178371.35669572458225.870153594
2178473.34324409458275.901290534 2178719.6503798458368.266466424
#Sta/Elev= 30
       0 3659.05     4.2 3657.25    18.9 3652.41    27.6 3647.87    39.5 3642.46
    44.1 3639.87      54 3632.29    62.6 3626.94    78.8  3619.1      90 3613.02
   101.2 3608.69  107.633606.971   112.3 3605.98   116.8 3605.86  123.233606.972
     139 3608.72   152.4  3608.7   179.1 3612.54     188 3612.97   209.6  3613.1
   226.7 3612.39   254.4 3612.93   265.8 3612.75   282.3 3611.58   296.4 3612.22
   356.9  3618.9   379.7 3619.62   401.9 3621.82   425.3 3625.54   456.9 3631.88
#Mann= 5 ,-1,0
       0     .12       0  107.63    .045       0  123.23      .1       0
   213.8     .12       0   433.8      .1       0
Bank Sta=107.63,123.23
XS Rating Curve= 0 ,0
Exp/Cntr(USF)=0,0
Exp/Cntr=0.3,0.1

Type RM Length L Ch R = 1 ,22970   ,394.5,405.6,423.2
XS GIS Cut Line= 4
2178286.68861782458431.7675248492178379.05379371458470.253014803
2178461.79759711458437.5403483422178706.18045832458501.041406766
#Sta/Elev= 30
       0 3651.31    27.6 3637.58    40.6 3633.45    49.3 3629.57    66.6 3623.12
    79.6  3620.2   105.6 3617.05   114.1  3614.8   118.5 3612.22   127.1 3605.38
  130.383603.938   144.3 3602.68   157.2    3603  160.943603.938   170.1 3606.26
   179.1 3607.55   216.3 3610.06   224.6  3609.6   261.8 3609.87   290.7 3608.77
   319.6 3606.62   340.3 3607.16   365.1 3611.43   381.6 3618.98     394 3623.06
   398.1 3623.89   410.5 3628.41   418.8 3629.57   426.9 3633.21   441.5 3638.05
#Mann= 5 ,-1,0
       0      .1       0  130.38    .045       0  160.94      .1       0
  229.04     .12       0  359.04      .1       0
#XS Ineff= 2 , 0
                          213.42         3610.82
Permanent Ineff=
       F       F
Bank Sta=130.38,160.94
XS Rating Curve= 0 ,0
Exp/Cntr(USF)=0,0
Exp/Cntr=0.3,0.1

Type RM Length L Ch R = 1 ,22564   ,213.5,213.1,213.2
XS GIS Cut Line= 4
2178255.90022585 458674.226111562178507.98018505458807.001051901
2178592.64826295 458858.956463342178663.84641937458901.290502289
#Sta/Elev= 30
       0 3639.71    11.3  3637.2      35 3626.22    67.5 3613.58    81.7 3610.19
    95.3 3607.78   100.8 3607.24   176.6 3605.64   194.7 3602.52   199.2  3602.3
   226.4 3603.15     258 3602.47     267 3603.28   277.8 3603.26   289.5 3601.45
   296.7 3602.59   303.2 3602.59   308.6 3602.35  324.33 3599.65   327.4 3598.87
   333.2 3598.58   341.9 3598.85  345.683599.649   350.3 3602.26   359.3 3610.59
   364.9 3614.91   369.6 3616.34   382.6 3622.42   435.1  3633.4   467.1 3638.46
#Mann= 4 ,-1,0
       0     .12       0     270      .1       0  324.33    .045       0
  345.68      .1       0
#XS Ineff= 2 , 0
          275.03 3605.83
Permanent Ineff=
       F       F
Bank Sta=324.33,345.68
XS Rating Curve= 0 ,0
Exp/Cntr(USF)=0,0
Exp/Cntr=0.3,0.1

Type RM Length L Ch R = 1 ,22351   ,210,209.5,208.8
XS GIS Cut Line= 4
2178180.85352044458785.8340324272178332.87120576458901.290502289
2178421.38783266458960.9430117182178538.76857702459059.081011101
#Sta/Elev= 30
       0 3640.45     7.6 3637.17    49.4 3622.75    79.5 3614.97   110.4 3607.82
   121.8 3606.19   144.6 3605.07   156.1 3605.21   174.9 3603.77   219.1 3603.55
   224.9 3602.33   227.8 3600.33  232.093596.206   233.6 3595.12   247.9 3595.03
  256.113596.209   262.3  3597.4   285.4 3599.61     298 3600.52   310.5 3600.68
     331 3604.23   347.9 3605.69   356.6 3605.69   367.9 3604.55   379.1    3607
   385.3 3610.72   395.1 3613.59   405.5 3615.17   426.4 3619.82   450.6 3622.85
#Mann= 4 ,-1,0
       0     .12       0  232.09    .045       0  256.11     .12       0
  270.89      .1       0
Bank Sta=232.09,256.11
XS Rating Curve= 0 ,0
Exp/Cntr(USF)=0,0
Exp/Cntr=0.3,0.1

Type RM Length L Ch R = 1 ,22141   ,309.9,312.1,310.5
XS GIS Cut Line= 4
2178078.86697207458970.5643842072178255.90022585459099.490775553
2178371.35669572459172.6132064662178417.53928366459201.477323932
#Sta/Elev= 30
       0 3634.33    11.4 3628.58    16.5 3627.61      20 3626.25    36.3 3617.83
      56 3610.18    75.8  3605.4    85.7 3603.57    94.4 3601.17   111.6 3600.13
   147.1 3599.98   164.9 3599.04   177.5 3599.15   194.7 3598.59   233.5 3599.45
   238.3 3598.31   250.13593.558   252.5 3592.67   257.2 3592.39   266.7 3592.56
  272.913593.557   285.6 3594.84   299.8 3594.97   328.2 3593.88   342.2 3594.73
   350.9 3599.45   365.4 3609.57   375.5  3614.9   389.7 3621.48   410.1 3627.71
#Mann= 6 ,-1,0
       0     .12       0     170      .1       0   250.1    .045       0
  272.91     .12       0     349      .1       0  385.67     .12       0
Bank Sta=250.1,272.91
XS Rating Curve= 0 ,0
Exp/Cntr(USF)=0,0
Exp/Cntr=0.3,0.1

Type RM Length L Ch R = 1 ,21829   ,265.7,267.5,268.8
XS GIS Cut Line= 4
 2177967.2590512459172.613206466 2178130.8223835459336.176538771
2178240.50602987459424.6931656662178305.93136279459474.724302606
#Sta/Elev= 30
       0 3617.08    12.6 3612.34    35.2 3605.34    46.3 3602.76    57.6  3601.1
    94.4 3598.16   103.1 3597.07   142.2 3596.43   153.5 3595.62   167.9  3595.8
   176.2 3595.03   187.7 3592.38   204.9 3590.11   239.3 3590.04   284.5 3591.69
   294.7 3588.27  303.233586.568   306.9 3585.84   315.3 3585.56  322.053586.568
   332.5 3588.91   349.6 3591.14   361.6 3591.29   376.9 3596.76   381.9    3600
   386.9 3604.66   400.9  3615.1   425.7 3632.11   438.9 3639.63   454.6 3645.99
#Mann= 4 ,-1,0
       0     .12       0     190      .1       0  303.23    .045       0
  322.05      .1       0
#XS Ineff= 2 , 0
          284.93 3593.89
Permanent Ineff=
       F       F
Bank Sta=303.23,322.05
XS Rating Curve= 0 ,0
Exp/Cntr(USF)=0,0
Exp/Cntr=0.3,0.1

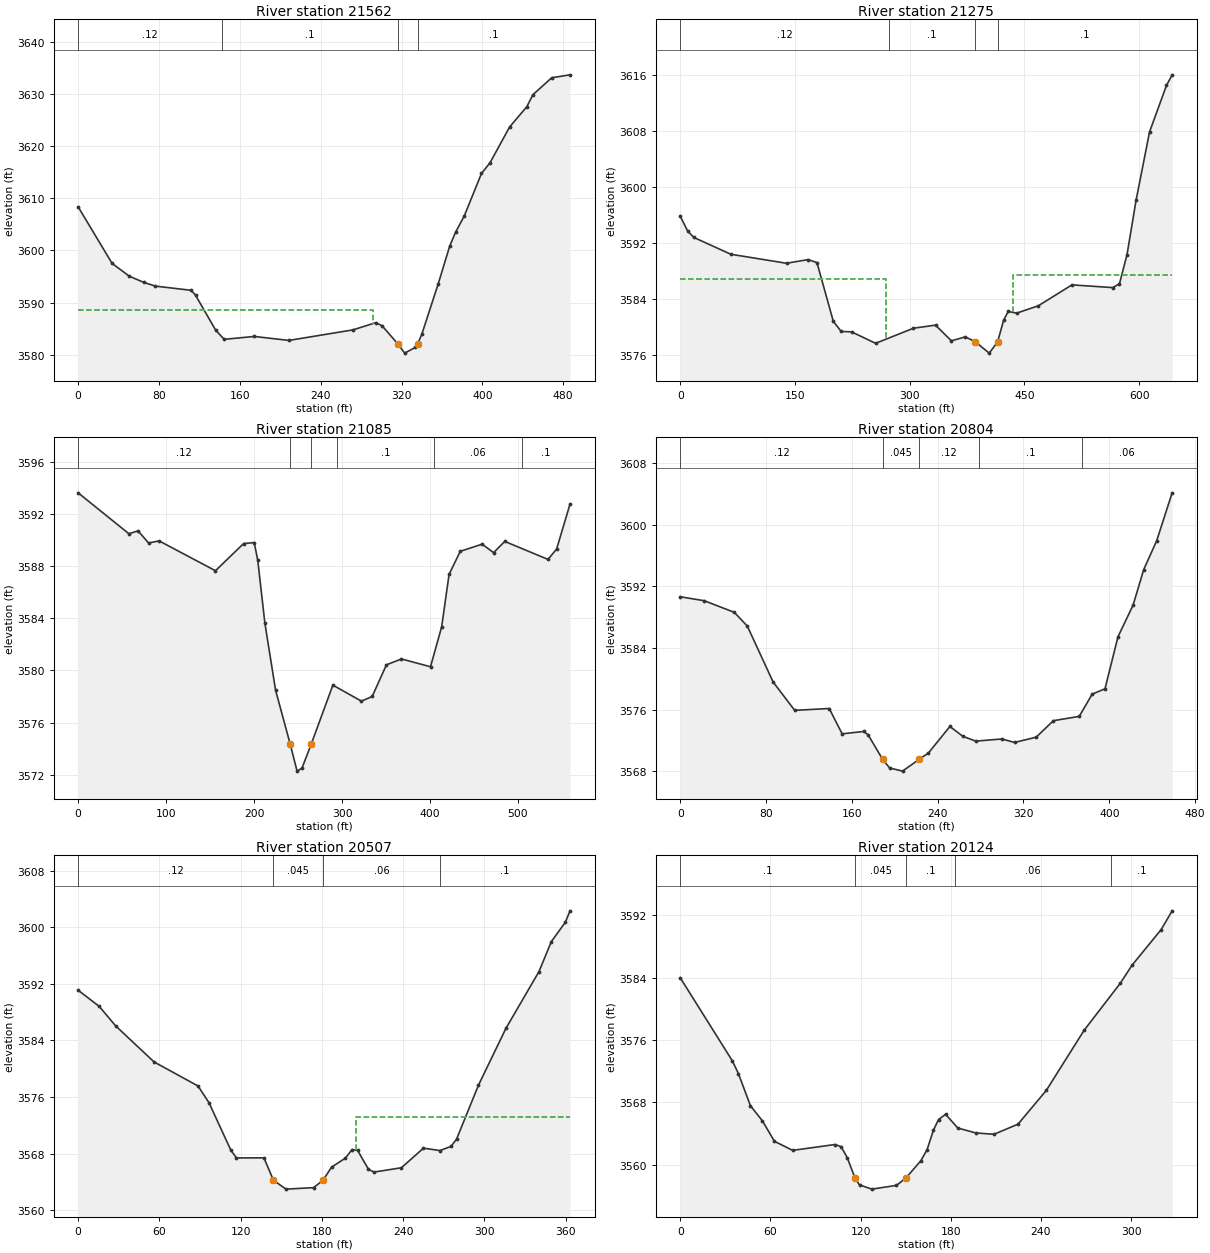
Type RM Length L Ch R = 1 ,21562   ,281.3,286.5,295
XS GIS Cut Line= 4
2177817.16564038459365.0406562372177886.43952229459453.557283131
2178075.01842307459640.2119094092178155.83795197459713.334340322
#Sta/Elev= 30
       0 3608.38    33.6 3597.52    50.7 3595.05    64.9 3593.88    76.4 3593.16
   111.9 3592.35   116.2  3591.4     136 3584.73   144.5 3582.94   174.4 3583.49
   208.5 3582.73   271.8 3584.75   294.4 3586.13   300.6 3585.57  316.083582.119
   323.1 3580.29   333.6 3581.38  336.033582.118     340 3583.89   356.4 3593.66
   367.7 3600.87   373.4 3603.47   382.1 3606.65   399.1 3614.79   407.6 3616.86
   426.9 3623.71     444 3627.62     450 3629.92   468.6 3633.17   486.7 3633.73
#Mann= 4 ,-1,0
       0     .12       0   142.4      .1       0  316.08    .045       0
  336.03      .1       0
#XS Ineff= 2 , 0
          291.53 3588.55
Permanent Ineff=
       F       F
Bank Sta=316.08,336.03
XS Rating Curve= 0 ,0
Exp/Cntr(USF)=0,0
Exp/Cntr=0.3,0.1

Type RM Length L Ch R = 1 ,21275   ,178,189.7,205.6
XS GIS Cut Line= 5
2177740.19466047459451.6330086342177765.21022894459632.514811418
2177888.36379679459871.1248491342177928.77356124 459950.02010354
2178023.06301163459992.354142489
#Sta/Elev= 30
       0 3595.82     9.6 3593.73    17.7  3592.8    66.2  3590.4   138.9 3589.12
   167.1 3589.64   178.7 3589.22   200.1 3580.84   210.4  3579.4     224 3579.34
   255.4 3577.71   304.9 3579.86   333.7  3580.3   354.5 3578.06   372.6 3578.63
   385.9 3577.92   403.9 3576.31  414.873577.905   422.8 3581.01   428.8 3582.25
   439.9 3582.01   468.3 3583.07   512.1 3586.04   565.4 3585.65   574.2 3586.19
   584.1 3590.34   595.9 3598.08   613.6 3607.86   635.7 3614.47   643.1 3615.98
#Mann= 4 ,-1,0
       0     .12       0   272.6      .1       0   385.9    .045       0
  414.87      .1       0
#XS Ineff= 2 , 0
           268.6 3586.83  434.88         3587.44
Permanent Ineff=
       F       F
Bank Sta=385.9,414.87
XS Rating Curve= 0 ,0
Exp/Cntr(USF)=0,0
Exp/Cntr=0.3,0.1

Type RM Length L Ch R = 1 ,21085   ,281.8,281.1,279.6
XS GIS Cut Line= 4
2177720.95191549459465.1029301182177726.72473898459669.076026875
2177697.86062152459826.8665356872177636.28383759460011.596887467
#Sta/Elev= 30
       0 3593.63    57.7 3590.49    68.1 3590.71    80.1 3589.78    92.1 3589.94
   156.1 3587.65   188.2 3589.74   200.2 3589.81   204.2 3588.45   212.3 3583.63
   224.5 3578.47  240.993574.366   248.9 3572.27   254.5  3572.5  265.123574.366
   289.6 3578.87   322.1 3577.64   334.3    3578   350.5 3580.43   367.6 3580.88
   400.6 3580.28   413.3 3583.35   421.7 3587.37   434.4 3589.14   459.3 3589.69
   472.3 3589.04     485  3589.9   534.2 3588.52     544 3589.32   559.2 3592.77
#Mann= 6 ,-1,0
       0     .12       0  240.99    .045       0  265.12     .12       0
  294.05      .1       0  404.46     .06       0  504.46      .1       0
Bank Sta=240.99,265.12
XS Rating Curve= 0 ,0
Exp/Cntr(USF)=0,0
Exp/Cntr=0.3,0.1

Type RM Length L Ch R = 1 ,20804   ,294.6,297.1,297.6
XS GIS Cut Line= 4
2177461.96349464459486.9787044422177451.40506118459595.202647386
 2177427.6485859459830.1277918252177419.72976081459943.630951498
#Sta/Elev= 30
       0 3590.63    22.3 3590.12    50.4 3588.61    62.5 3586.83    86.6 3579.57
   106.7  3575.9   138.9 3576.14   150.9 3572.86     171 3573.16   175.1 3572.74
  188.66 3569.55   195.2 3568.43   207.2 3568.02  222.76 3569.55   231.3 3570.36
   251.4 3573.81   263.5 3572.53   275.6 3571.91   299.7 3572.19   311.7 3571.74
   331.8 3572.42   347.9 3574.56     372 3575.12     384    3578     396  3578.7
   408.1 3585.45   422.2 3589.55   432.1 3594.16   444.2  3597.9   458.6 3604.11
#Mann= 5 ,-1,0
       0     .12       0  188.66    .045       0  222.76     .12       0
  278.74      .1       0  374.86     .06       0
Bank Sta=188.66,222.76
XS Rating Curve= 0 ,0
Exp/Cntr(USF)=0,0
Exp/Cntr=0.3,0.1

Type RM Length L Ch R = 1 ,20507   ,382,382.9,382.9
XS GIS Cut Line= 4
2177176.38223264459497.8155965792177160.98803666459594.029321464
 2177130.1996447459767.2140262582177114.80544871459855.730653152
#Sta/Elev= 30
       0 3591.09    15.6  3588.8    27.7 3586.05    56.1 3580.95    88.5 3577.56
    96.6  3575.2   112.8 3568.47   116.9 3567.39   137.2  3567.4  144.243564.219
   153.5 3562.98   173.8 3563.19  180.773564.218   187.1 3566.08   197.4 3567.37
   202.2 3568.56   206.3 3568.47   214.4 3565.78   218.5 3565.39   238.7    3566
     255 3568.77   267.2 3568.43   275.3 3569.02   279.4 3570.03   295.6 3577.67
   315.9 3585.71   340.3 3593.73   349.4 3597.96   359.8 3600.71   363.2 3602.31
#Mann= 4 ,-1,0
       0     .12       0  144.24    .045       0  180.77     .06       0
  267.44      .1       0
#XS Ineff= 2 , 0
                          205.06         3573.18
Permanent Ineff=
       F       F
Bank Sta=144.24,180.77
XS Rating Curve= 0 ,0
Exp/Cntr(USF)=0,0
Exp/Cntr=0.3,0.1

Type RM Length L Ch R = 1 ,20124   ,505.2,503.2,497.2
XS GIS Cut Line= 4
 2176789.6030586459478.5728516022176783.83023511459570.938027492
2176764.58749013459663.3032033812176760.73894114459803.775241714
#Sta/Elev= 30
       0 3583.99    34.7 3573.33    38.7 3571.71    46.7 3567.59    54.7 3565.64
    62.7 3563.02    74.8 3561.86     103 3562.61   107.1 3562.33   111.2  3560.9
  116.263558.326   119.3 3557.43   127.5 3556.89   143.9 3557.37  150.263558.327
   160.2 3560.55   164.3 3561.96   168.5 3564.45   171.9 3565.81   176.6 3566.49
   184.7 3564.73   196.6  3564.1   208.8 3563.92   224.8 3565.22   243.6 3569.54
   268.8 3577.26   292.8 3583.27   300.8 3585.63   320.1 3590.18   327.4 3592.58
#Mann= 5 ,-1,0
       0      .1       0  116.26    .045       0  150.26      .1       0
  182.55     .06       0  286.89      .1       0
Bank Sta=116.26,150.26
XS Rating Curve= 0 ,0
Exp/Cntr(USF)=0,0
Exp/Cntr=0.3,0.1

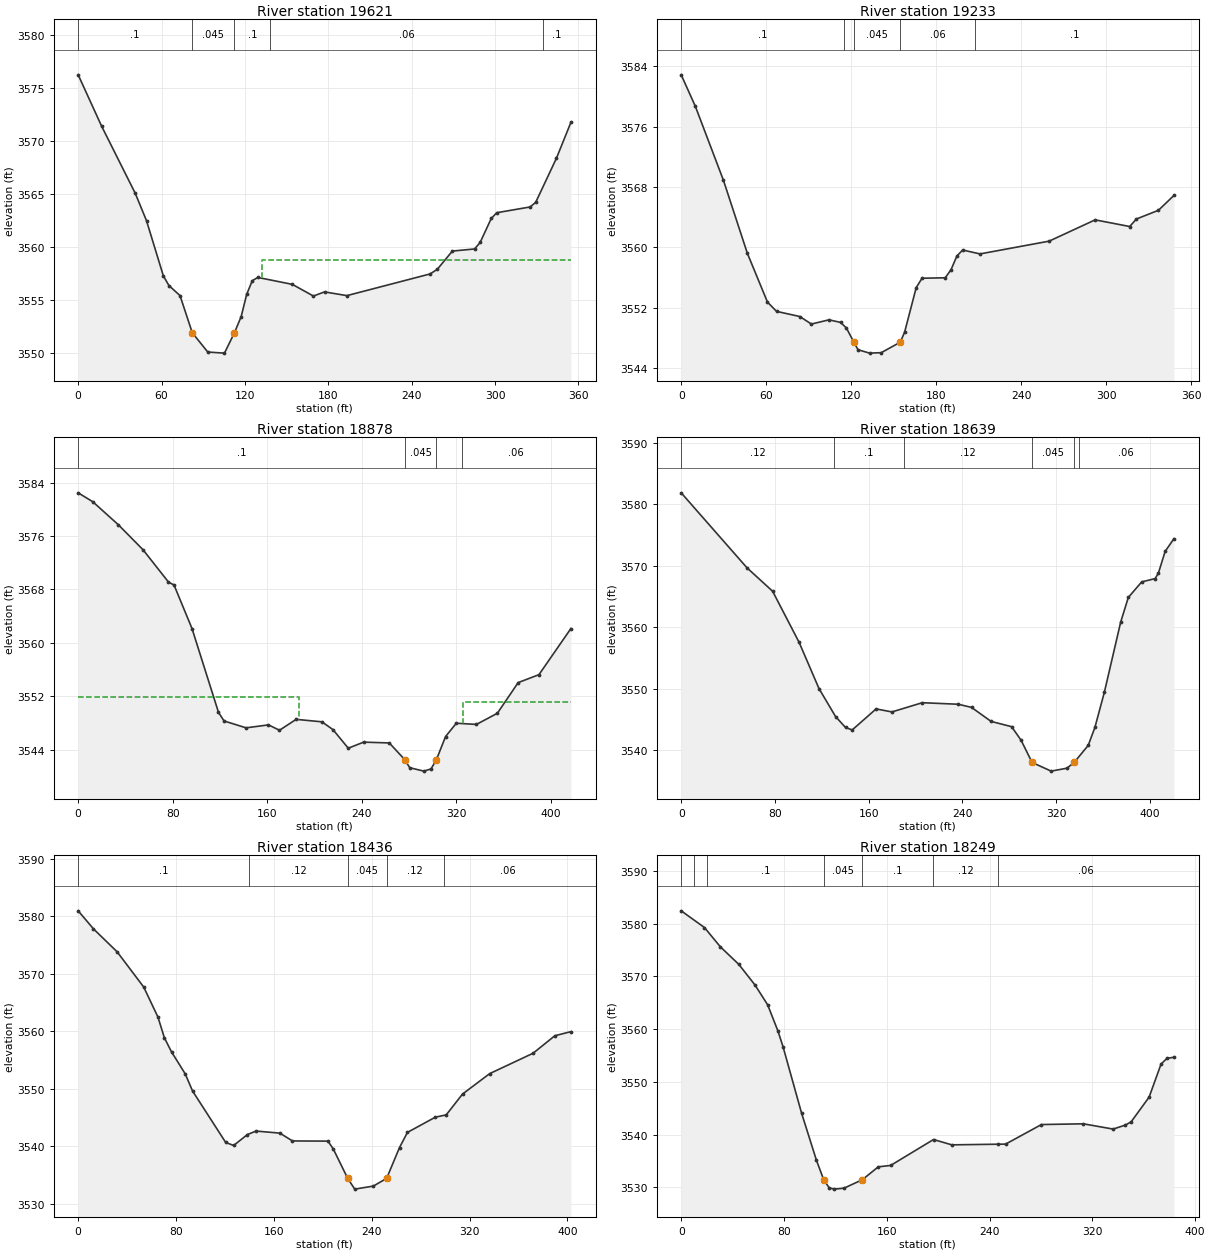
Type RM Length L Ch R = 1 ,19621   ,383.3,388.3,392.8
XS GIS Cut Line= 4
2176295.06451269459432.390263657 2176287.3674147459490.118498588
 2176287.3674147459586.3322234732176291.21596369459786.456771235
#Sta/Elev= 30
       0 3576.21    16.9 3571.37    41.1 3565.06    49.2 3562.48    61.3  3557.3
    65.3 3556.39    73.3 3555.44   82.123551.945    93.3 3550.13   105.3 3550.03
  112.463551.947   117.3 3553.46   121.3 3555.57   125.3 3556.84   129.3 3557.15
   154.1  3556.5   169.3  3555.4   177.3 3555.79   193.4 3555.44   253.3 3557.48
   258.5 3557.92   269.3 3559.63   285.3 3559.83   289.3 3560.44   297.3  3562.7
   301.3 3563.24   325.3 3563.78   329.3 3564.22   344.2 3568.36   354.6 3571.73
#Mann= 5 ,-1,0
       0      .1       0   82.12    .045       0  112.46      .1       0
  138.24     .06       0  334.45      .1       0
#XS Ineff= 2 , 0
                          132.01         3558.77
Permanent Ineff=
       F       F
Bank Sta=82.12,112.46
XS Rating Curve= 0 ,0
Exp/Cntr(USF)=0,0
Exp/Cntr=0.3,0.1

Type RM Length L Ch R = 1 ,19233   ,351.9,354.8,357.2
XS GIS Cut Line= 4
2175940.99800511459361.1921072412175925.60380913459403.526146191
2175890.96686817459551.695282514 2175864.0270252459699.864418838
#Sta/Elev= 30
       0 3582.86      10 3578.68    29.8  3568.9    46.7 3559.22    60.9 3552.76
    67.3 3551.53    83.7 3550.85    91.9 3549.85   104.3 3550.41   112.5 3550.07
   116.6 3549.33   121.93547.446   124.8 3546.45     133    3546   141.2 3546.06
  154.643547.448   157.7 3548.77   165.9 3554.68     170 3555.92   186.4 3555.98
   190.5 3557.06   194.6 3558.86   198.7 3559.66   210.9 3559.14   259.7 3560.83
   292.2 3563.65   316.6 3562.77   321.3 3563.76   336.9 3564.92   347.8 3566.88
#Mann= 5 ,-1,0
       0      .1       0  115.05     .06       0   121.9    .045       0
  154.64     .06       0  207.21      .1       0
Bank Sta=121.9,154.64
XS Rating Curve= 0 ,0
Exp/Cntr(USF)=0,0
Exp/Cntr=0.3,0.1

Type RM Length L Ch R = 1 ,18878   ,233.1,239,244.5
XS GIS Cut Line= 4
2175694.69086941459184.1588534522175592.70432103459349.646460255
2175540.74890959459474.7243026062175504.18769413459553.619557012
#Sta/Elev= 30
       0 3582.46    12.4 3581.12    34.1 3577.66    54.9 3573.93    76.4  3569.1
    81.1 3568.66    96.3 3562.14   118.7  3549.6   123.4 3548.31     142 3547.28
     161 3547.72   170.3 3546.92   184.4 3548.55   206.2 3548.18   215.5 3547.02
   228.5 3544.23   241.5 3545.14   263.2 3545.02  276.273542.519   280.5 3541.31
   292.4  3540.8   298.5 3541.13  303.073542.518   310.8 3545.98   319.9 3547.97
   336.9 3547.79   354.6 3549.46   372.2 3554.05   389.8 3555.24   416.8 3562.14
#Mann= 4 ,-1,0
       0      .1       0  276.27    .045       0  303.07      .1       0
  324.39     .06       0
#XS Ineff= 2 , 0
          186.47 3551.89  325.63         3551.21
Permanent Ineff=
       F       F
Bank Sta=276.27,303.07
XS Rating Curve= 0 ,0
Exp/Cntr(USF)=0,0
Exp/Cntr=0.3,0.1

Type RM Length L Ch R = 1 ,18639   ,189.4,203.1,212.2
XS GIS Cut Line= 4
2175569.61302705459076.3994815812175398.35259676459257.281284365
2175319.45734235459355.4192837482175292.51749938459391.980499205
#Sta/Elev= 30
       0 3581.88    56.2 3569.67      78 3565.87   100.6 3557.56   117.6 3550.03
   131.7 3545.49   140.2 3543.71   145.9 3543.31   166.3 3546.73   179.8 3546.24
   205.7 3547.74   236.4 3547.49   247.7 3546.98   264.4  3544.7   281.9 3543.84
     290 3541.64  299.383538.019   315.7 3536.61   329.2 3537.09  335.28 3538.02
   347.3  3540.8     353 3543.72   361.1 3549.47     375 3560.86   381.5 3564.86
   392.9 3567.39   404.4 3567.93   407.2 3568.83   412.9 3572.34   420.4 3574.42
#Mann= 6 ,-1,0
       0     .12       0     130      .1       0     190     .12       0
  299.38    .045       0  335.28     .12       0   339.1     .06       0
Bank Sta=299.38,335.28
XS Rating Curve= 0 ,0
Exp/Cntr(USF)=0,0
Exp/Cntr=0.3,0.1

Type RM Length L Ch R = 1 ,18436   ,196.4,186.7,172.3
XS GIS Cut Line= 4
2175436.83808671458982.1100311932175305.98742087 459118.73352053
2175223.24361747459153.3704614892175169.36393153459264.978382356
#Sta/Elev= 30
       0 3580.97    12.5 3577.83    31.9 3573.82    53.6 3567.69    65.2 3562.48
    70.5 3558.85    76.3 3556.41    87.5 3552.59    93.5  3549.6   120.6 3540.64
   127.1 3540.11   138.4 3542.02   145.5 3542.62   164.9 3542.26   175.2  3540.9
   204.2 3540.87   208.5 3539.53  220.353534.379   226.1 3532.51   241.3 3533.04
  252.18 3534.38   262.7 3539.75   269.2 3542.39     292 3545.04   300.9 3545.44
   314.2 3549.06   336.4 3552.62   371.9 3556.17   389.7 3559.22   402.8 3559.93
#Mann= 5 ,-1,0
       0      .1       0     140     .12       0  220.35    .045       0
  252.18     .12       0  298.88     .06       0
Bank Sta=220.35,252.18
XS Rating Curve= 0 ,0
Exp/Cntr(USF)=0,0
Exp/Cntr=0.3,0.1

Type RM Length L Ch R = 1 ,18249   ,276.1,271.9,266.1
XS GIS Cut Line= 4
2175252.10773493458870.5021103262175207.84942148458932.078894252
2175136.65126507459041.7625406222175046.21036368459193.780225941
#Sta/Elev= 30
       0 3582.45    18.1 3579.28    30.5 3575.62    44.9 3572.28    57.5 3568.36
    67.3 3564.62    75.3 3559.65    79.3 3556.64    93.7 3544.07   105.3 3535.11
  110.913531.444   115.3 3529.88   119.3 3529.66   126.7 3529.84  140.963531.441
   153.4 3533.89     163 3534.15   196.4 3539.07   210.6 3538.06   246.6 3538.18
   252.5  3538.2   280.4 3541.91     313 3542.05   336.2 3541.05   345.6  3541.8
   350.2 3542.42   364.2 3547.11   373.5 3553.38   378.1 3554.47   383.5 3554.67
#Mann= 7 ,-1,0
       0      .1       0      10     .12       0      20      .1       0
  110.91    .045       0  140.96      .1       0  195.83     .12       0
   246.6     .06       0
Bank Sta=110.91,140.96
XS Rating Curve= 0 ,0
Exp/Cntr(USF)=0,0
Exp/Cntr=0.3,0.1