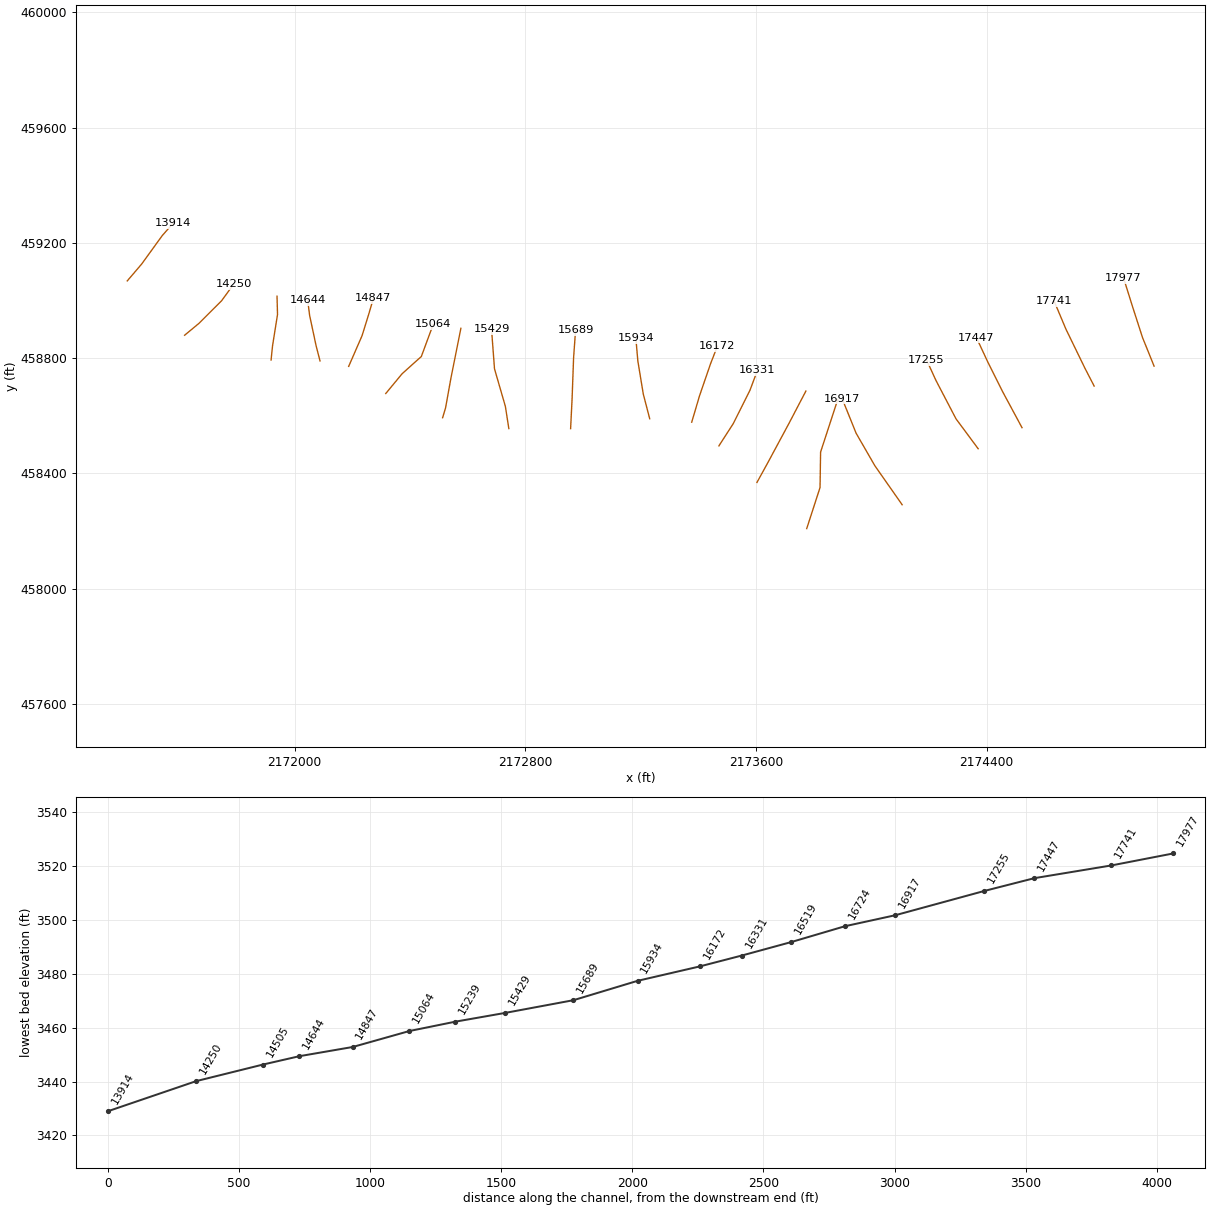
HEC-RAS study NFCRNBRYRV.prj: NFCRNBRYRV

--- NFCRNBRYRV.g01 (geometry) --- (continued)

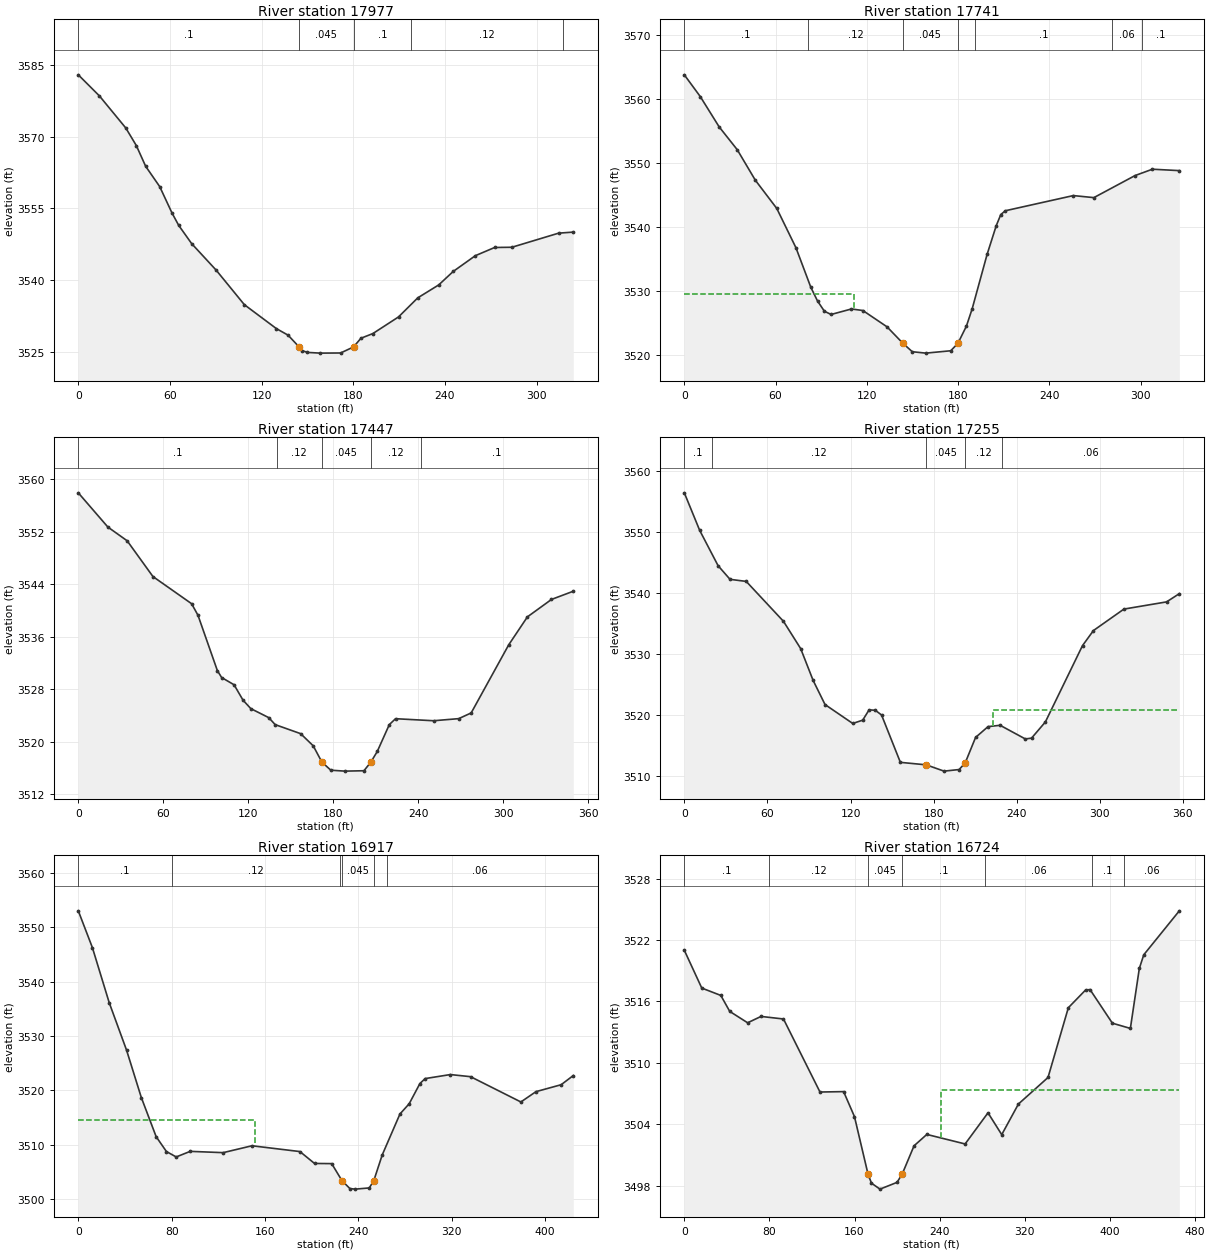
Type RM Length L Ch R = 1 ,17977   ,233.4,236.3,239.7
XS GIS Cut Line= 4
2174980.78503076458772.364110943 2174940.3752663458872.426384824
2174903.81405085458985.9585801882174874.94993338459078.323756078
#Sta/Elev= 30
       0 3582.92    13.8 3578.52    31.1  3571.8      38 3568.12    44.1 3563.79
    53.3 3559.54    61.3 3554.05    65.7 3551.45    74.2 3547.62    90.2 3542.09
   108.7 3534.85   129.7 3529.84   137.3 3528.48  144.543526.013   146.5 3525.25
     150 3524.87   158.4 3524.72   171.7 3524.75  180.163526.013     185 3527.83
   192.8 3528.81   209.6 3532.29   222.2 3536.28   235.9 3538.98   245.4  3541.8
   259.9  3545.1   272.5 3546.81   283.8 3546.86   314.4 3549.81     324 3550.03
#Mann= 5 ,-1,0
       0      .1       0  144.54    .045       0  180.16      .1       0
  217.91     .12       0  317.19     .06       0
Bank Sta=144.54,180.16
XS Rating Curve= 0 ,0
Exp/Cntr(USF)=0,0
Exp/Cntr=0.3,0.1

Type RM Length L Ch R = 1 ,17741   ,293.5,294,293.9
XS GIS Cut Line= 4
  2174772.963385458703.0902290252174740.25071854 458766.59128745
2174674.82538562458901.2905022892174634.41562117458997.504227175
#Sta/Elev= 30
       0 3563.75    10.5 3560.35    22.9 3555.62    34.8 3552.05    46.7 3547.28
    60.8 3542.87    73.4 3536.73    83.2 3530.54    87.6  3528.4    92.1 3526.81
    96.5  3526.3   109.9 3527.16   117.4 3526.92   133.3 3524.37  143.72  3521.8
   149.9 3520.48   158.8 3520.26   175.2 3520.63  179.923521.798   185.5 3524.48
   189.3  3527.2   199.1 3535.69   205.1 3540.17   208.1 3541.91   211.1 3542.51
   255.8 3544.88   269.3 3544.56   296.4 3548.01   307.8    3549   325.5 3548.78
#Mann= 7 ,-1,0
       0      .1       0   81.43     .12       0  143.72    .045       0
  179.92     .12       0  191.43      .1       0  281.18     .06       0
  301.18      .1       0
#XS Ineff= 2 , 0
          111.66 3529.55
Permanent Ineff=
       F       F
Bank Sta=143.72,179.92
XS Rating Curve= 0 ,0
Exp/Cntr(USF)=0,0
Exp/Cntr=0.3,0.1

Type RM Length L Ch R = 1 ,17447   ,191,191.8,191.7
XS GIS Cut Line= 4
 2174522.8077003458558.7696416972174455.45809288458683.847484048
2174405.42695594458783.9097579292174365.01719149458870.502110326
#Sta/Elev= 30
       0 3557.95    20.9 3552.73    34.5 3550.64    52.7 3545.19      80 3541.05
    84.5 3539.29    98.2 3530.85   101.2  3529.8     110 3528.69   116.3 3526.35
   121.8 3525.06   134.5 3523.68     139 3522.62     157 3521.24   165.9 3519.38
  171.983516.915   178.3 3515.67   188.3 3515.53   201.7 3515.59   206.63516.917
   211.1 3518.53   219.6 3522.62     224 3523.52   250.9 3523.21   268.6 3523.53
   277.4  3524.4   303.9 3534.78   317.1 3539.04   334.1  3541.7   349.5 3542.95
#Mann= 5 ,-1,0
       0      .1       0     140     .12       0  171.98    .045       0
   206.6     .12       0  242.06      .1       0
Bank Sta=171.98,206.6
XS Rating Curve= 0 ,0
Exp/Cntr(USF)=0,0
Exp/Cntr=0.3,0.1

Type RM Length L Ch R = 1 ,17255   ,336.7,338.3,338
XS GIS Cut Line= 4
2174370.79001498458485.6472107842174293.81903507458589.558033661
2174224.54515316458722.332974002 2174191.8324867458793.531130418
#Sta/Elev= 30
       0 3556.41    11.1 3550.25    24.4 3544.45      33 3542.22    44.7 3541.88
    71.6 3535.33      84 3530.86      93 3525.64   101.6 3521.68   121.6 3518.58
   128.8 3519.12   133.4 3520.81   137.9 3520.74   142.4 3519.97     156  3512.2
   174.7 3511.79   187.5 3510.76   198.4 3511.02  202.783512.101   210.3 3516.29
   219.3 3518.06     228 3518.28   246.2 3516.04   250.7 3516.17   260.7 3518.83
   287.5 3531.35   295.4 3533.82   317.4 3537.34   348.2 3538.52   357.4 3539.87
#Mann= 5 ,-1,0
       0      .1       0      20     .12       0   174.7    .045       0
  202.78     .12       0  229.31     .06       0
#XS Ineff= 2 , 0
                          222.66         3520.76
Permanent Ineff=
       F       F
Bank Sta=174.7,202.78
XS Rating Curve= 0 ,0
Exp/Cntr(USF)=0,0
Exp/Cntr=0.3,0.1

Type RM Length L Ch R = 1 ,16917   ,199.4,192.7,176
XS GIS Cut Line= 4
 2174107.1644088458291.2954865162174012.87495841458425.994701355
2173947.44962549 458539.526896722173899.34276304458658.831915578
#Sta/Elev= 30
       0 3553.06    12.1 3546.27    26.5 3536.13    41.4 3527.36      54 3518.66
    66.7 3511.45    75.5 3508.71    83.9 3507.71    95.9 3508.74   124.1  3508.5
   148.8 3509.77   189.9  3508.7   202.4 3506.51   217.1 3506.48   225.93503.348
   232.7 3501.88   237.3 3501.78   249.3    3502  253.19 3503.35   260.4 3508.08
   275.6 3515.63   283.5 3517.51   292.7 3521.24   297.2 3522.15   318.8 3522.89
   336.1  3522.5   379.2 3517.84   392.1 3519.74   413.7 3521.02   424.1 3522.71
#Mann= 6 ,-1,0
       0      .1       0      80     .12       0  224.42      .1       0
   225.9    .045       0  253.19      .1       0  264.42     .06       0
#XS Ineff= 2 , 0
          151.27 3514.45
Permanent Ineff=
       F       F
Bank Sta=225.9,253.19
XS Rating Curve= 0 ,0
Exp/Cntr(USF)=0,0
Exp/Cntr=0.3,0.1

Type RM Length L Ch R = 1 ,16724   ,207.8,204.8,189.8
XS GIS Cut Line= 4
2173776.18919519458208.5516831142173822.37178314458350.947995945
2173824.29605763458474.1015637982173883.94856706 458656.90764108
#Sta/Elev= 30
       0    3521    16.4 3517.31    34.3 3516.59    42.7 3515.03    59.5 3513.92
    72.1 3514.54    93.2 3514.29   127.5 3507.16   149.7  3507.2   159.9 3504.76
  172.65 3499.14   175.9 3498.26   183.9 3497.68   199.9 3498.34  204.72 3499.14
   215.9 3501.91   227.9 3503.02   263.9 3502.09   285.4 3505.13   298.3    3503
     314 3505.99   341.8 3508.58   360.9 3515.39   377.1 3517.12   381.3 3517.16
   402.3 3513.88   419.2 3513.37   427.6 3519.22   431.8 3520.56   465.2 3524.85
#Mann= 7 ,-1,0
       0      .1       0      80     .12       0  172.65    .045       0
  204.72      .1       0  282.87     .06       0  382.87      .1       0
  412.87     .06       0
#XS Ineff= 2 , 0
                          240.86         3507.37
Permanent Ineff=
       F       F
Bank Sta=172.65,204.72
XS Rating Curve= 0 ,0
Exp/Cntr(USF)=0,0
Exp/Cntr=0.3,0.1

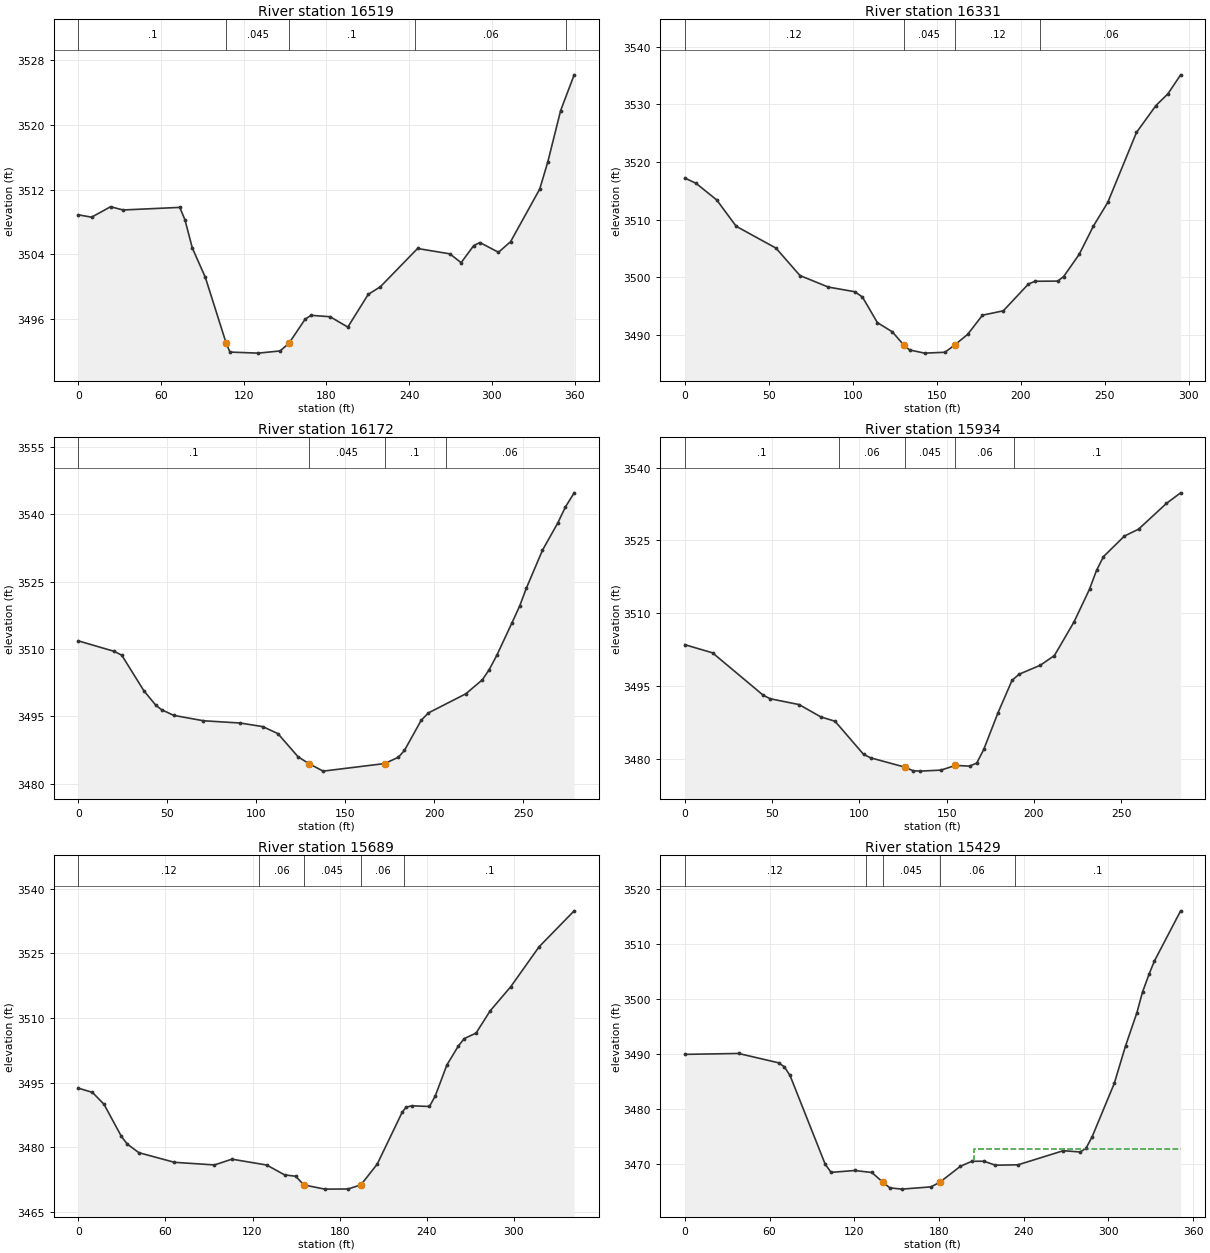
Type RM Length L Ch R = 1 ,16519   ,189.5,188.1,184.4
XS GIS Cut Line= 4
2173603.60822179458368.6845487552173641.31820375458437.248152327
2173715.02407759 458574.375359472173773.30314063458685.791215274
#Sta/Elev= 30
       0 3508.89     9.6  3508.6    23.4 3509.89    32.5 3509.49    73.6 3509.81
    77.4 3508.25    82.7 3504.79    92.1 3501.18  107.313493.001     110 3491.93
   130.5  3491.8   146.3 3492.07  152.763493.002   164.5 3495.99   168.8 3496.47
   182.6  3496.3   195.5 3495.02   210.3 3499.06   219.1    3500   246.1 3504.73
   269.5 3504.07   277.7 3502.98   286.8 3505.08   291.3 3505.47   304.8 3504.26
   313.6 3505.58   334.7 3512.07   340.6 3515.44   349.9 3521.78   359.7 3526.19
#Mann= 5 ,-1,0
       0      .1       0  107.31    .045       0  152.76      .1       0
  243.93     .06       0  353.93      .1       0
Bank Sta=107.31,152.76
XS Rating Curve= 0 ,0
Exp/Cntr(USF)=0,0
Exp/Cntr=0.3,0.1

Type RM Length L Ch R = 1 ,16331   ,157.7,159.8,166.8
XS GIS Cut Line= 4
2173471.62328491458495.527215363 2173521.3318975458572.661269381
2173579.61096054458689.2193954532173605.32231188458757.782999025
#Sta/Elev= 30
       0 3517.22     6.7  3516.3      19 3513.42    30.6 3508.84    54.3 3505.05
    68.6 3500.28    85.5 3498.28   101.3 3497.47   105.8 3496.55   114.7 3492.11
   123.6 3490.51  130.393488.222   133.9 3487.36   142.8 3486.81     155 3486.96
  160.713488.222   168.4 3490.05   177.3  3493.4   189.7 3494.16   204.6  3498.8
   208.6 3499.29   222.1 3499.32   225.6  3500.1   234.9 3503.97   243.4  3508.9
   251.9 3512.98     269 3525.13   280.6 3529.81   287.7 3531.83   295.3 3535.14
#Mann= 4 ,-1,0
       0     .12       0  130.39    .045       0  160.71     .12       0
  211.76     .06       0
Bank Sta=130.39,160.71
XS Rating Curve= 0 ,0
Exp/Cntr(USF)=0,0
Exp/Cntr=0.3,0.1

Type RM Length L Ch R = 1 ,16172   ,230.3,238,251.8
XS GIS Cut Line= 4
   2173377.34833458577.8035396492173404.77377143458670.364404471
2173442.48375339458780.0661701862173466.48101464  458841.7734134
#Sta/Elev= 30
       0 3511.79    20.2 3509.45    24.4  3508.6    36.9 3500.65    43.6 3497.43
    46.8 3496.46    53.6  3495.2    70.3    3494    91.1 3493.49   103.7 3492.69
   112.2 3491.13   123.5 3485.98  129.543484.465   137.6 3482.78  172.143484.464
   179.9 3485.87   183.3 3487.39   192.7 3494.09   196.8 3495.75   217.8    3500
   227.1 3503.12   230.9 3505.36   235.2 3508.55   243.8 3515.86   248.1 3519.58
   251.8  3523.5   260.9 3531.99   269.5 3538.05   273.8 3541.62   278.7 3544.76
#Mann= 4 ,-1,0
       0      .1       0  129.54    .045       0  172.14      .1       0
  206.54     .06       0
Bank Sta=129.54,172.14
XS Rating Curve= 0 ,0
Exp/Cntr(USF)=0,0
Exp/Cntr=0.3,0.1

Type RM Length L Ch R = 1 ,15934   ,246.7,244.3,239
XS GIS Cut Line= 4
2173231.65067241458589.8021702742173209.36750125458675.506674739
2173190.51251027458790.3507107222173183.65614991458869.198854829
#Sta/Elev= 30
       0 3503.48    15.9  3501.8      45 3493.04      49 3492.33    65.5 3491.13
    77.9  3488.6    86.1 3487.69   102.4 3480.88   106.5 3480.15   125.9 3478.25
   130.8 3477.49   134.8 3477.41   146.8 3477.62   155.1 3478.59   163.2 3478.44
   167.3 3479.08   171.3 3481.89   179.4 3489.39   187.5 3496.13   191.6  3497.4
   203.7 3499.24   211.8 3501.25   223.1 3508.23   231.9 3514.93   235.9 3518.79
   239.9 3521.64   251.9 3525.88     260  3527.3     276 3532.62   284.1 3534.79
#Mann= 5 ,-1,0
       0      .1       0   88.55     .06       0   125.9    .045       0
   155.1     .06       0  188.55      .1       0
Bank Sta=125.9,155.1
XS Rating Curve= 0 ,0
Exp/Cntr(USF)=0,0
Exp/Cntr=0.3,0.1

Type RM Length L Ch R = 1 ,15689   ,253.2,260.8,268.9
XS GIS Cut Line= 4
2172957.39625812458555.5203684882172962.53852839458660.079863935
2172967.68079866458800.6352512572172974.53715902458896.624296258
#Sta/Elev= 30
       0 3493.69     9.7 3492.71    17.7 3489.94    29.7 3482.46    33.7  3480.7
    41.7  3478.7    66.2 3476.46    93.8 3475.85   105.8 3477.19   129.8 3475.83
   142.1 3473.54   149.8 3473.22  155.27 3471.22   169.8 3470.23   185.8 3470.26
  194.663471.219   205.9 3476.03   223.2 3488.15   225.9 3489.29   229.9 3489.59
   241.9 3489.43   245.9 3491.87   253.9 3499.07   261.9 3503.53   265.9 3505.21
     274 3506.48   283.7 3511.64     298  3517.3   317.4 3526.52   341.6 3534.89
#Mann= 5 ,-1,0
       0     .12       0  124.69     .06       0  155.27    .045       0
  194.66     .06       0  224.69      .1       0
Bank Sta=155.27,194.66
XS Rating Curve= 0 ,0
Exp/Cntr(USF)=0,0
Exp/Cntr=0.3,0.1

Type RM Length L Ch R = 1 ,15429   ,196.4,189.3,178.4
XS GIS Cut Line= 4
2172743.13499696458555.5203684882172731.13636634458632.654422506
2172693.42638437458762.9252692932172683.14184384458900.052476436
#Sta/Elev= 30
       0 3489.95    38.1 3490.11    66.4 3488.42    70.5 3487.69    74.5 3486.14
    99.4 3470.05   103.6 3468.54   120.3 3468.88   132.5 3468.52  140.283466.759
   145.2 3465.74   153.6  3465.5   174.4 3465.91  180.683466.759   195.2 3469.64
   203.4 3470.56   211.9 3470.56     220 3469.84     236 3469.91   268.1 3472.47
   280.1 3472.24   284.2 3472.92   288.5 3474.99   304.2 3484.68   312.2  3491.5
   320.2 3497.49   324.2 3501.25   328.9 3504.54   332.6 3506.87   351.2 3515.99
#Mann= 5 ,-1,0
       0     .12       0  128.06     .06       0  140.28    .045       0
  180.68     .06       0  233.68      .1       0
#XS Ineff= 2 , 0
                          204.81         3472.77
Permanent Ineff=
       F       F
Bank Sta=140.28,180.68
XS Rating Curve= 0 ,0
Exp/Cntr(USF)=0,0
Exp/Cntr=0.3,0.1

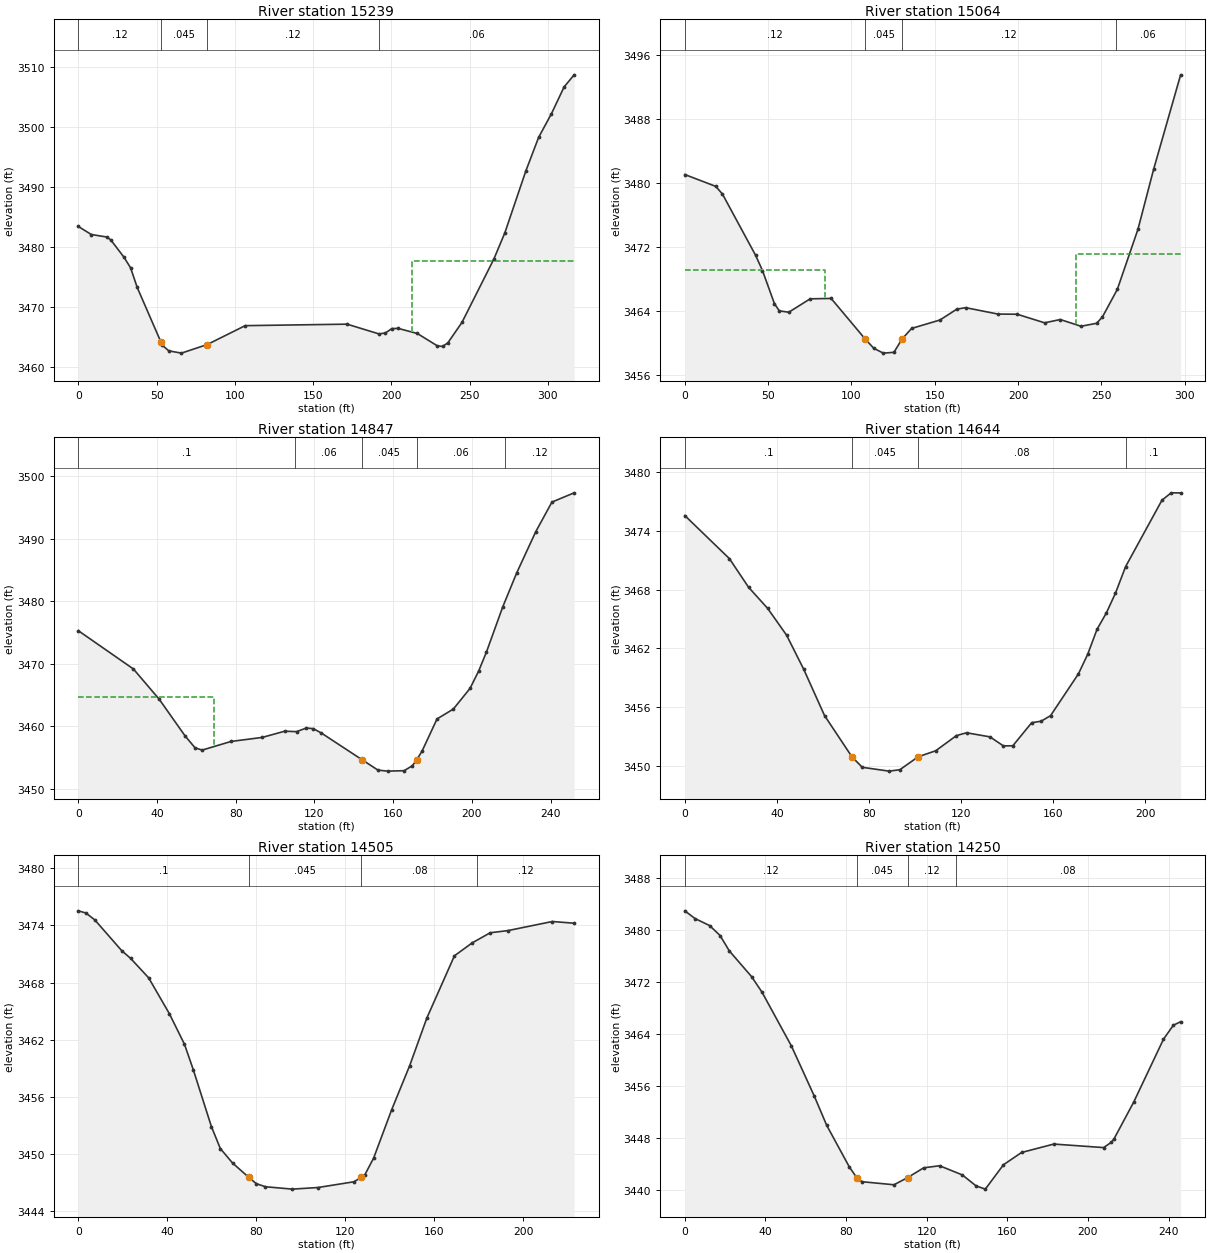
Type RM Length L Ch R = 1 ,15239   ,186.7,175.7,161.4
XS GIS Cut Line= 4
  2172513.446925458593.2303504532172523.73146553458627.512152239
2172542.58645651458732.071647686 2172576.8682583458903.480656615
#Sta/Elev= 30
       0 3483.42     8.3 3482.08    18.2 3481.66    20.8 3481.16    29.2 3478.27
    33.4 3476.51    37.6 3473.25   52.713464.144    53.7 3463.57    57.8 3462.64
    65.9 3462.26    82.4  3463.7   106.6 3466.85   171.7  3467.1   192.1 3465.47
   196.2 3465.63   200.3 3466.36   204.4 3466.39   216.6 3465.54   229.3 3463.49
   232.7 3463.37   236.1 3463.98   245.1 3467.38   265.5 3477.98   272.5 3482.35
   285.9 3492.68   294.1 3498.31   302.3 3502.27   310.4 3506.75   316.8 3508.76
#Mann= 4 ,-1,0
       0     .12       0   52.71    .045       0    82.4     .12       0
  192.04     .06       0
#XS Ineff= 2 , 0
                          213.37         3477.68
Permanent Ineff=
       F       F
Bank Sta=52.71,82.4
XS Rating Curve= 0 ,0
Exp/Cntr(USF)=0,0
Exp/Cntr=0.3,0.1

Type RM Length L Ch R = 1 ,15064   ,206.9,216.3,227.3
XS GIS Cut Line= 4
2172316.32656473458677.2207648282172372.89153767  458745.7843684
2172439.74105116458805.777521525 2172480.8792133458917.193377329
#Sta/Elev= 30
       0 3481.05    18.6 3479.57    22.6 3478.61    42.5 3470.97    46.6 3469.08
    53.8 3464.94    56.7 3464.05    62.4 3463.88    75.2 3465.55    87.8  3465.6
  108.233460.537   113.4 3459.38   119.1 3458.78   125.5 3458.88  130.333460.535
   136.1 3461.86   153.1 3462.91   163.2 3464.26   168.5 3464.45   187.9 3463.65
   199.4 3463.63   215.9 3462.56   225.3 3462.97   237.7 3462.13   247.1  3462.5
   250.6  3463.3   259.5 3466.72   271.9 3474.22   281.3  3481.7   297.5 3493.48
#Mann= 4 ,-1,0
       0     .12       0  108.23    .045       0  130.33     .12       0
  258.71     .06       0
#XS Ineff= 2 , 0
           84.16 3469.12  234.72          3471.1
Permanent Ineff=
       F       F
Bank Sta=108.23,130.33
XS Rating Curve= 0 ,0
Exp/Cntr(USF)=0,0
Exp/Cntr=0.3,0.1

Type RM Length L Ch R = 1 ,14847   ,194.2,203.1,213.1
XS GIS Cut Line= 4
2172187.76980803458771.4957197392172234.05024044458877.769305276
2172258.04750169458954.903359294 2172273.4743125459008.040152062
#Sta/Elev= 30
       0 3475.29      28 3469.17    41.1 3464.34    54.2  3458.5    59.3 3456.58
    62.9 3456.21    77.6 3457.59    93.5 3458.24   104.9 3459.23   110.9 3459.16
   115.9 3459.74   119.5 3459.63   123.5 3458.94  144.163454.679   152.3 3453.01
   157.2 3452.85   165.6 3452.92   169.8 3453.72     1723454.679   174.7 3456.05
   182.3 3461.19   190.6 3462.77   199.1 3466.08   203.5 3468.87   207.4 3471.86
   215.7 3479.09   222.8 3484.53   232.5 3491.12   240.7 3495.84     252 3497.32
#Mann= 5 ,-1,0
       0      .1       0     110     .06       0  144.16    .045       0
     172     .06       0  216.69     .12       0
#XS Ineff= 2 , 0
           68.77 3464.63
Permanent Ineff=
       F       F
Bank Sta=144.16,172
XS Rating Curve= 0 ,0
Exp/Cntr(USF)=0,0
Exp/Cntr=0.3,0.1

Type RM Length L Ch R = 1 ,14644   ,146.9,139,133.5
XS GIS Cut Line= 4
2172088.35258285458790.3507107222172074.63986214 458843.48750349
2172052.35669098458948.0469989372172045.50033062459001.183791705
#Sta/Elev= 30
       0 3475.56    19.4 3471.15    27.7 3468.23      36 3466.07    44.2 3463.34
    51.7 3459.83    60.7 3455.12   72.613450.904    77.1 3449.83    88.7 3449.44
    93.4 3449.58  101.383450.906     109 3451.52     118 3453.07   122.4 3453.36
   132.6 3452.94   138.4 3452.02   142.5 3452.03   150.7 3454.39   154.8 3454.54
   158.9 3455.11     171 3459.38     175 3461.36   179.1 3463.94   183.1 3465.59
   187.1 3467.63   191.5 3470.34   207.3 3477.13   211.3 3477.88   215.4 3477.87
#Mann= 4 ,-1,0
       0      .1       0   72.61    .045       0  101.38     .08       0
  191.79      .1       0
Bank Sta=72.61,101.38
XS Rating Curve= 0 ,0
Exp/Cntr(USF)=0,0
Exp/Cntr=0.3,0.1

Type RM Length L Ch R = 1 ,14505   ,265.3,255,243.2
XS GIS Cut Line= 4
2171918.65766401  458793.77889092171923.79993428 458843.48750349
2171940.94083517458951.4751791152171939.22674508459014.896512419
#Sta/Elev= 30
       0 3475.53     3.4  3475.3     7.4 3474.58    19.5 3471.35    23.5 3470.54
    31.6  3468.5    40.9 3464.74    47.7 3461.53    51.7 3458.83    59.8 3452.89
    63.8 3450.59    69.3 3449.07   76.633447.557      80  3446.9    84.1 3446.58
    96.2 3446.33   107.7  3446.5   123.8  3447.1  127.183447.557   128.6 3447.77
   132.7 3449.59   140.8 3454.66   148.9 3459.29   156.6 3464.28     169 3470.81
     177 3472.17   185.1 3473.23   192.9 3473.45     213 3474.41   222.8 3474.23
#Mann= 4 ,-1,0
       0      .1       0   76.63    .045       0  127.18     .08       0
  179.31     .12       0
Bank Sta=76.63,127.18
XS Rating Curve= 0 ,0
Exp/Cntr(USF)=0,0
Exp/Cntr=0.3,0.1

Type RM Length L Ch R = 1 ,14250   ,322,336.5,335.4
XS GIS Cut Line= 4
2171618.69189838458879.4833953652171668.40051097458920.621557508
2171747.24865508458999.4697016162171788.38681722459056.034674562
#Sta/Elev= 30
       0 3482.91     5.1 3481.72    12.3 3480.65    17.5 3479.12    22.1 3476.75
    33.1 3472.82    38.3 3470.42    52.9 3462.15    64.2 3454.49    70.4 3449.97
    81.7 3443.54   85.473441.865    87.9 3441.31   103.8 3440.84   110.6 3441.95
   118.5 3443.44   126.4 3443.76   137.7 3442.35   144.5 3440.67   149.1 3440.17
   158.1 3443.91   167.1  3445.8   183.1 3447.09   207.8 3446.55   211.6 3447.36
   212.8  3447.8   222.7 3453.52   237.5  3463.2   242.4 3465.34     246 3465.88
#Mann= 4 ,-1,0
       0     .12       0   85.47    .045       0   110.6     .12       0
  134.52     .08       0
Bank Sta=85.47,110.6
XS Rating Curve= 0 ,0
Exp/Cntr(USF)=0,0
Exp/Cntr=0.3,0.1

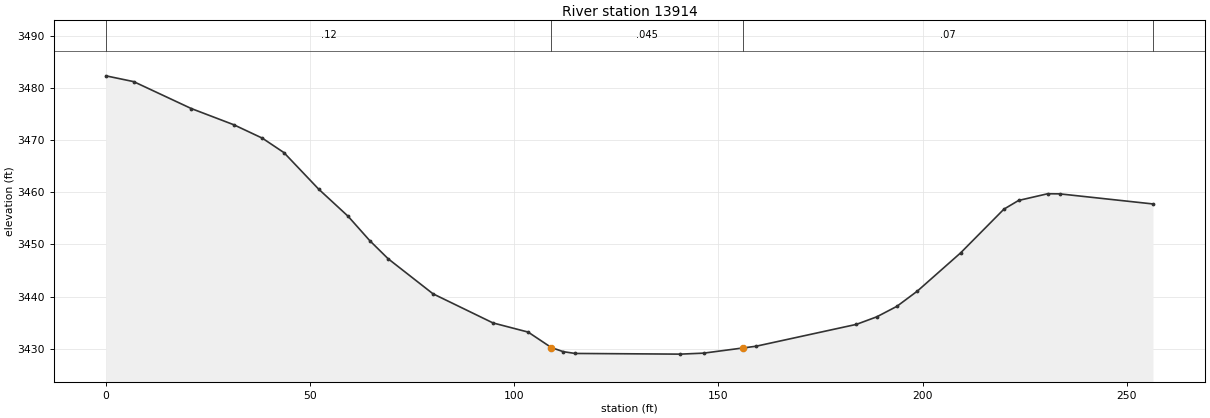
Type RM Length L Ch R = 1 ,13914   ,206.6,202.1,194
XS GIS Cut Line= 4
2171419.85744803459068.0333051872171469.56606062459126.312368223
2171541.55784437459225.7295934032171579.26782633459268.581845635
#Sta/Elev= 30
       0 3482.28     6.8 3481.17    20.9 3476.02    31.3 3472.92    38.3 3470.35
    43.6 3467.58    52.1 3460.59    59.3  3455.4    64.6 3450.74    69.1 3447.27
    80.1 3440.55    94.8 3434.97   103.4 3433.22  109.073430.263     112 3429.47
   114.9 3429.13   140.7    3429   146.4 3429.19   156.1 3430.19   159.2 3430.51
   183.8  3434.7   188.8 3436.15   193.7 3438.15   198.7 3441.06   209.3 3448.38
   219.9 3456.75   223.5 3458.42   230.6  3459.7   233.6 3459.68   256.4 3457.75
#Mann= 4 ,-1,0
       0     .12       0  109.07    .045       0   156.1     .07       0
  256.43      .1       0
Bank Sta=109.07,156.1
XS Rating Curve= 0 ,0
Exp/Cntr(USF)=0,0
Exp/Cntr=0.3,0.1