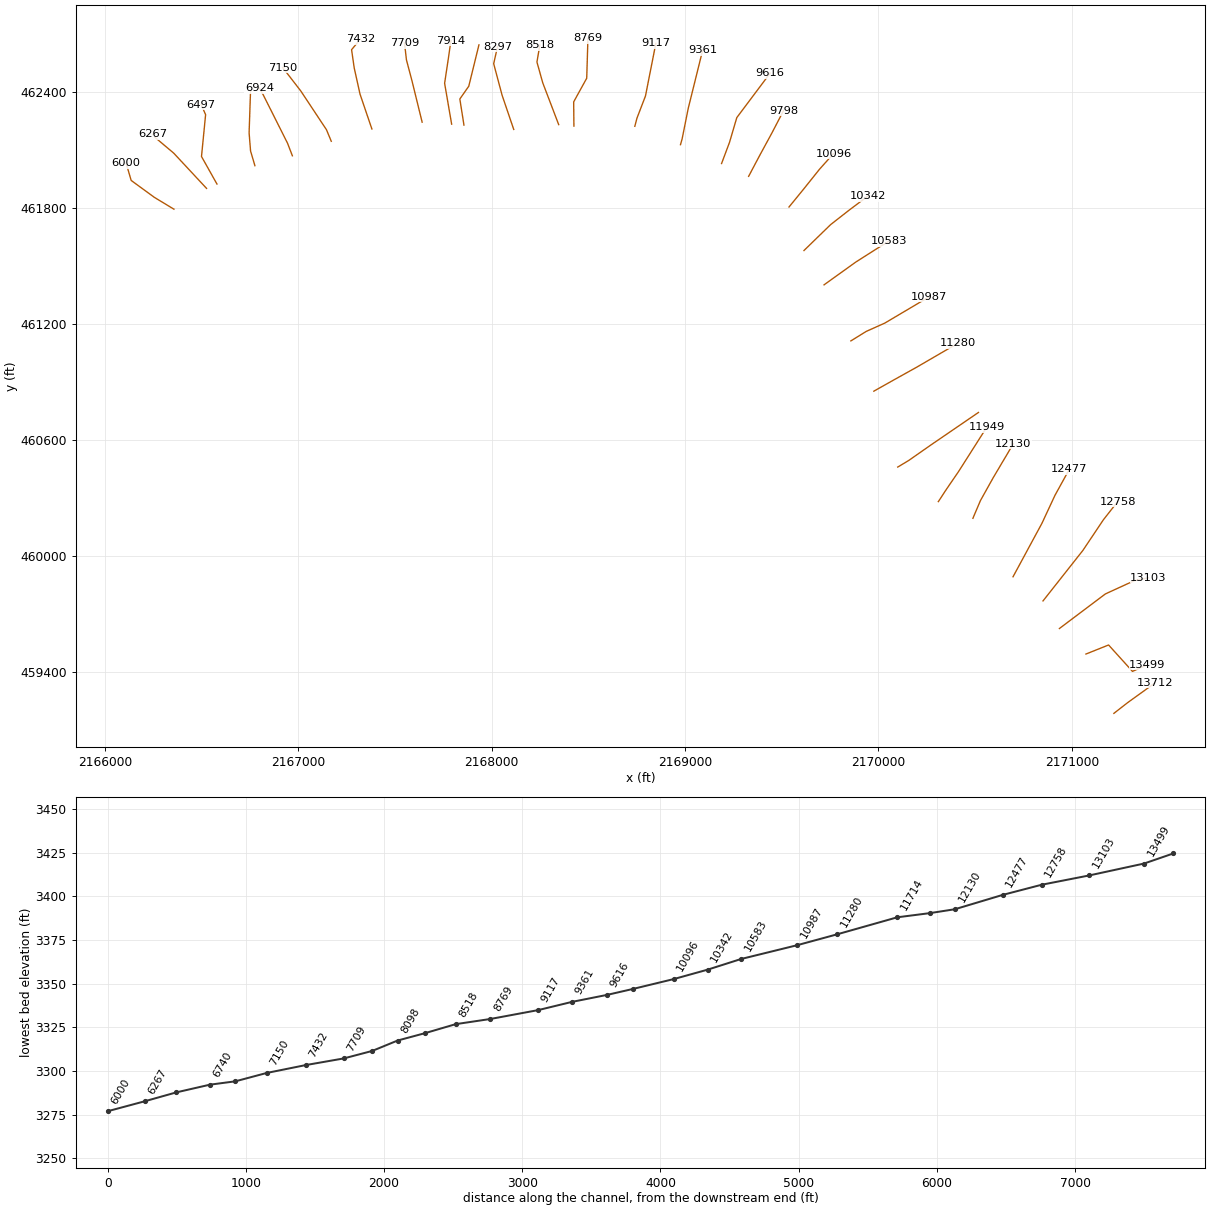
HEC-RAS study NFCRNBRYRV.prj: NFCRNBRYRV

--- NFCRNBRYRV.g01 (geometry) --- (continued)

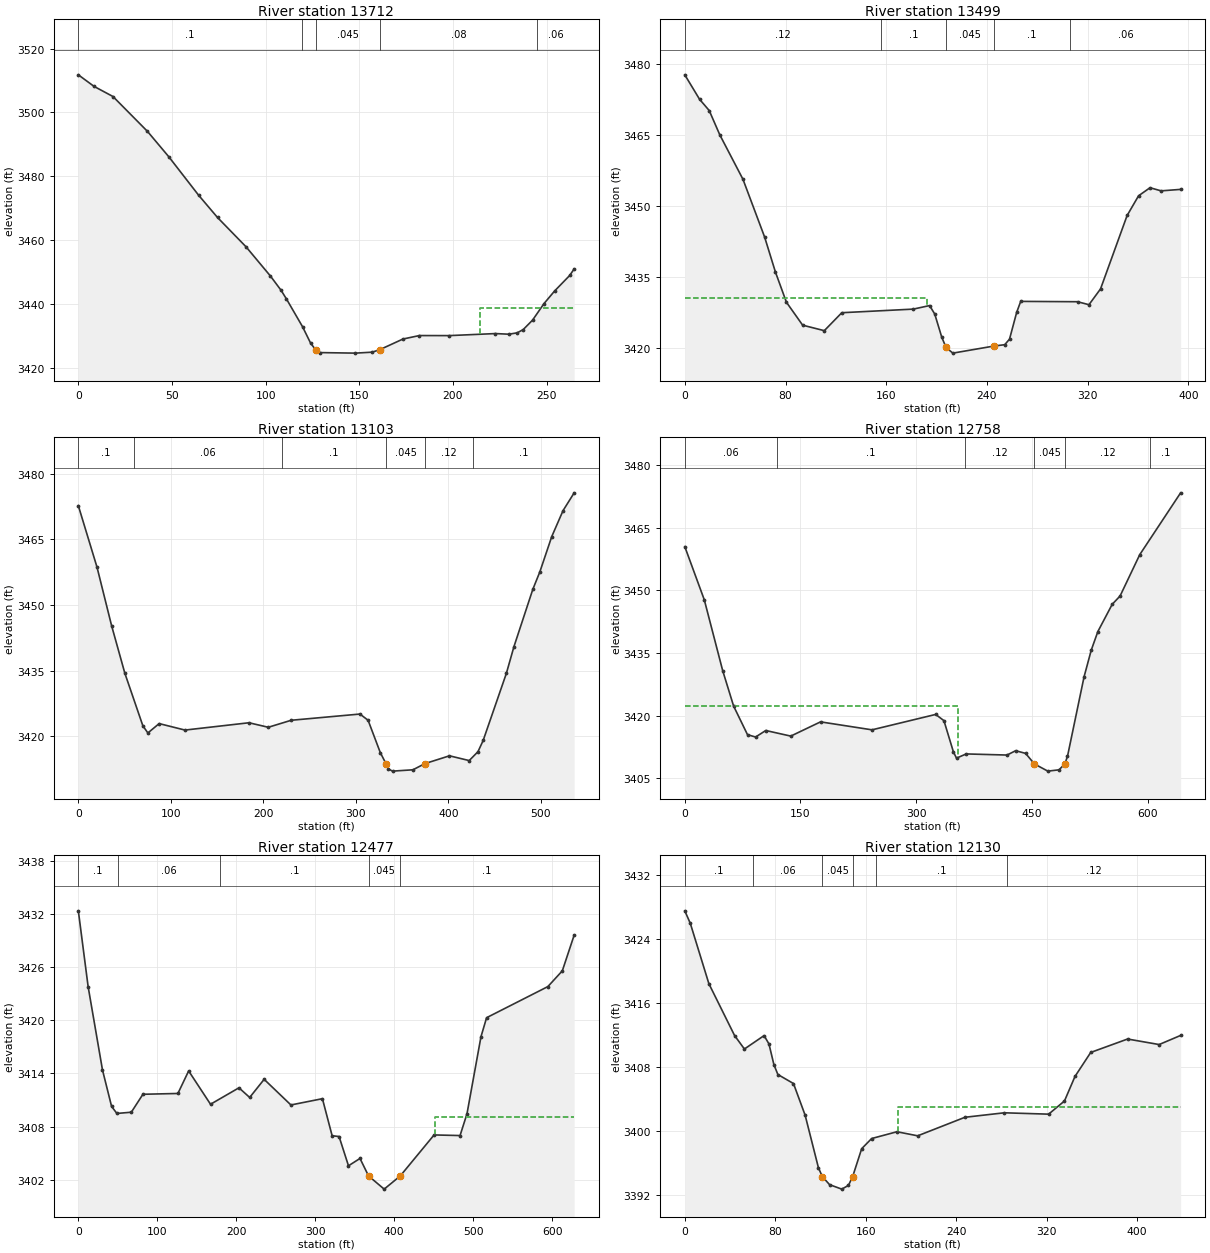
Type RM Length L Ch R = 1 ,13712   ,246.7,213.1,161.4
XS GIS Cut Line= 4
2171217.59481749459188.0196114382171287.87251115459242.870494296
2171373.57701562 459304.577737512171430.14198856459345.715899653
#Sta/Elev= 30
       0 3511.77     8.4 3508.15    18.5 3504.98    36.9 3494.08    48.3 3486.13
    64.2 3474.11    74.3 3467.13    89.5 3457.98   102.5 3448.85   108.2 3444.38
   111.1 3441.65   119.7 3432.95     124 3427.82  126.623425.789     129 3424.86
   147.9 3424.69   156.9 3424.99     161 3425.79   173.3  3429.1   182.1 3430.19
     198 3430.17   222.7 3430.81   229.8 3430.61   234.3 3431.04   237.5 3432.06
   242.5 3435.02   248.6 3440.19   254.3 3444.16   262.3 3448.98   264.7 3451.04
#Mann= 5 ,-1,0
       0      .1       0  119.15     .12       0  126.62    .045       0
     161     .08       0  244.76     .06       0
#XS Ineff= 2 , 0
                          214.19         3438.94
Permanent Ineff=
       F       F
Bank Sta=126.62,161
XS Rating Curve= 0 ,0
Exp/Cntr(USF)=0,0
Exp/Cntr=0.3,0.1

Type RM Length L Ch R = 1 ,13499   ,359.3,395.3,435.1
XS GIS Cut Line= 4
2171073.27883001459494.8499642822171190.23507961459541.632464122
2171313.68889863459405.1835062562171390.36021781459438.970867251
#Sta/Elev= 30
       0 3477.61    11.7 3472.46    19.4 3470.07    27.8 3464.94    46.2 3455.56
    63.4 3443.37      72 3435.97    80.7 3429.62    93.6 3424.77   110.8 3423.61
   124.7  3427.4   181.5 3428.16   194.4 3428.91   198.5 3427.13   204.1 3422.22
   207.5 3420.06   212.9 3418.87   245.2 3420.35   254.1 3420.65   257.9 3421.82
   263.6 3427.49   266.8 3429.79   311.9 3429.72     321 3429.09   330.2 3432.43
   351.3 3447.92   360.4 3452.08   369.5 3453.78   378.3 3453.12   393.8 3453.43
#Mann= 5 ,-1,0
       0     .12       0  155.97      .1       0   207.5    .045       0
   245.2      .1       0  305.97     .06       0
#XS Ineff= 2 , 0
          192.74 3430.47
Permanent Ineff=
       F       F
Bank Sta=207.5,245.2
XS Rating Curve= 0 ,0
Exp/Cntr(USF)=0,0
Exp/Cntr=0.3,0.1

Type RM Length L Ch R = 1 ,13103   ,326.3,345.1,352.5
XS GIS Cut Line= 4
2170936.07437531   459626.8780972171173.49299358459805.566846539
2171323.44159459459874.2932886692171395.91675175459889.288148771
#Sta/Elev= 30
       0 3472.72    20.2 3458.67      36 3445.28    50.3 3434.44    69.8 3422.42
    75.2  3420.8    87.4 3422.94   115.3 3421.46   184.5 3423.13   205.4  3422.1
   230.2  3423.7   304.5 3425.12   313.3  3423.7   326.5 3416.31  332.583413.805
   335.3 3412.57   339.7 3412.08   361.7 3412.38  374.883413.807   401.3 3415.58
   422.6 3414.49   432.1 3416.52   437.7 3419.08   462.8 3434.41     471 3440.52
   491.4 3453.61     499  3457.6   511.9 3465.68   524.1  3471.6   536.1 3475.66
#Mann= 6 ,-1,0
       0      .1       0      60     .06       0     220      .1       0
  332.58    .045       0  374.88     .12       0  427.15      .1       0
Bank Sta=332.58,374.88
XS Rating Curve= 0 ,0
Exp/Cntr(USF)=0,0
Exp/Cntr=0.3,0.1

Type RM Length L Ch R = 1 ,12758   ,274.4,281.5,282.1
XS GIS Cut Line= 4
2170851.10350141459769.329267961 2171057.2828278460030.489748056
2171163.49642018460189.1853507942171237.22114901460282.903226426
#Sta/Elev= 30
       0  3460.5    25.3 3447.75    49.1 3430.82    63.3 3422.31    81.3 3415.46
    91.8  3414.9     105 3416.46   137.4 3415.12     176 3418.53   242.7 3416.62
   325.3 3420.31     336 3418.82   348.3 3411.33   352.3 3409.84   364.9 3410.85
   417.8 3410.58     429 3411.62   441.9 3410.98  453.333408.446   470.7 3406.73
   485.2 3407.04  492.743408.446   496.2 3410.27   517.7 3429.32     527  3435.7
   535.6 3440.17   554.2 3446.69   564.4 3448.68   589.9 3458.58   642.9 3473.39
#Mann= 6 ,-1,0
       0     .06       0     120      .1       0  362.74     .12       0
  453.33    .045       0  492.74     .12       0   603.7      .1       0
#XS Ineff= 2 , 0
          354.65 3422.24
Permanent Ineff=
       F       F
Bank Sta=453.33,492.74
XS Rating Curve= 0 ,0
Exp/Cntr(USF)=0,0
Exp/Cntr=0.3,0.1

Type RM Length L Ch R = 1 ,12477   ,346.5,346.8,346.2
XS GIS Cut Line= 4
 2170696.1566137459894.2864354712170846.10521471460171.691347342
2170912.33251349460314.1425183032170987.30681399460450.345830889
#Sta/Elev= 30
       0  3432.4    12.4 3423.83    30.6 3414.39    42.1 3410.28    48.8 3409.48
    67.1 3409.62    81.8 3411.65   126.1 3411.74   139.7 3414.29   167.4 3410.52
   203.4 3412.38     217 3411.29   235.3 3413.34   269.2 3410.44   309.1 3411.15
   321.4 3406.96   330.2 3406.87   342.1 3403.56   356.7 3404.39  367.54 3402.41
   387.3 3400.92  407.653402.409   450.5 3407.05   483.4 3406.98   492.2 3409.45
   509.9 3418.16     517 3420.31   594.6 3423.83   612.9 3425.61   627.9 3429.65
#Mann= 5 ,-1,0
       0      .1       0      50     .06       0     180      .1       0
  367.54    .045       0  407.65      .1       0
#XS Ineff= 2 , 0
                          452.04         3409.07
Permanent Ineff=
       F       F
Bank Sta=367.54,407.65
XS Rating Curve= 0 ,0
Exp/Cntr(USF)=0,0
Exp/Cntr=0.3,0.1

Type RM Length L Ch R = 1 ,12130   ,182.8,181,177.3
XS GIS Cut Line= 4
2170488.72771563460196.6827808442170527.46443756460287.901513126
2170593.69173634 460406.610822262170697.40618537460581.550856774
#Sta/Elev= 30
       0 3427.51     4.9 3425.93    21.3 3418.39      44 3411.91    52.7 3410.22
    70.1  3411.9    74.4 3410.86    78.8 3408.26    82.3 3407.03    96.1  3405.9
   106.4 3401.94   118.2 3395.34  121.633394.255     128 3393.25   138.8 3392.69
   144.7 3393.16  148.413394.255   156.4 3397.75   165.2 3399.02   187.6 3399.87
   205.9 3399.36   247.7 3401.68   282.5 3402.24   321.7 3402.07   335.7 3403.72
     345 3406.79   358.9 3409.79   391.5 3411.47   419.4 3410.78   438.4 3411.92
#Mann= 6 ,-1,0
       0      .1       0      60     .06       0  121.63    .045       0
  148.41     .06       0   169.1      .1       0  285.04     .12       0
#XS Ineff= 2 , 0
                          188.67         3402.97
Permanent Ineff=
       F       F
Bank Sta=121.63,148.41
XS Rating Curve= 0 ,0
Exp/Cntr(USF)=0,0
Exp/Cntr=0.3,0.1

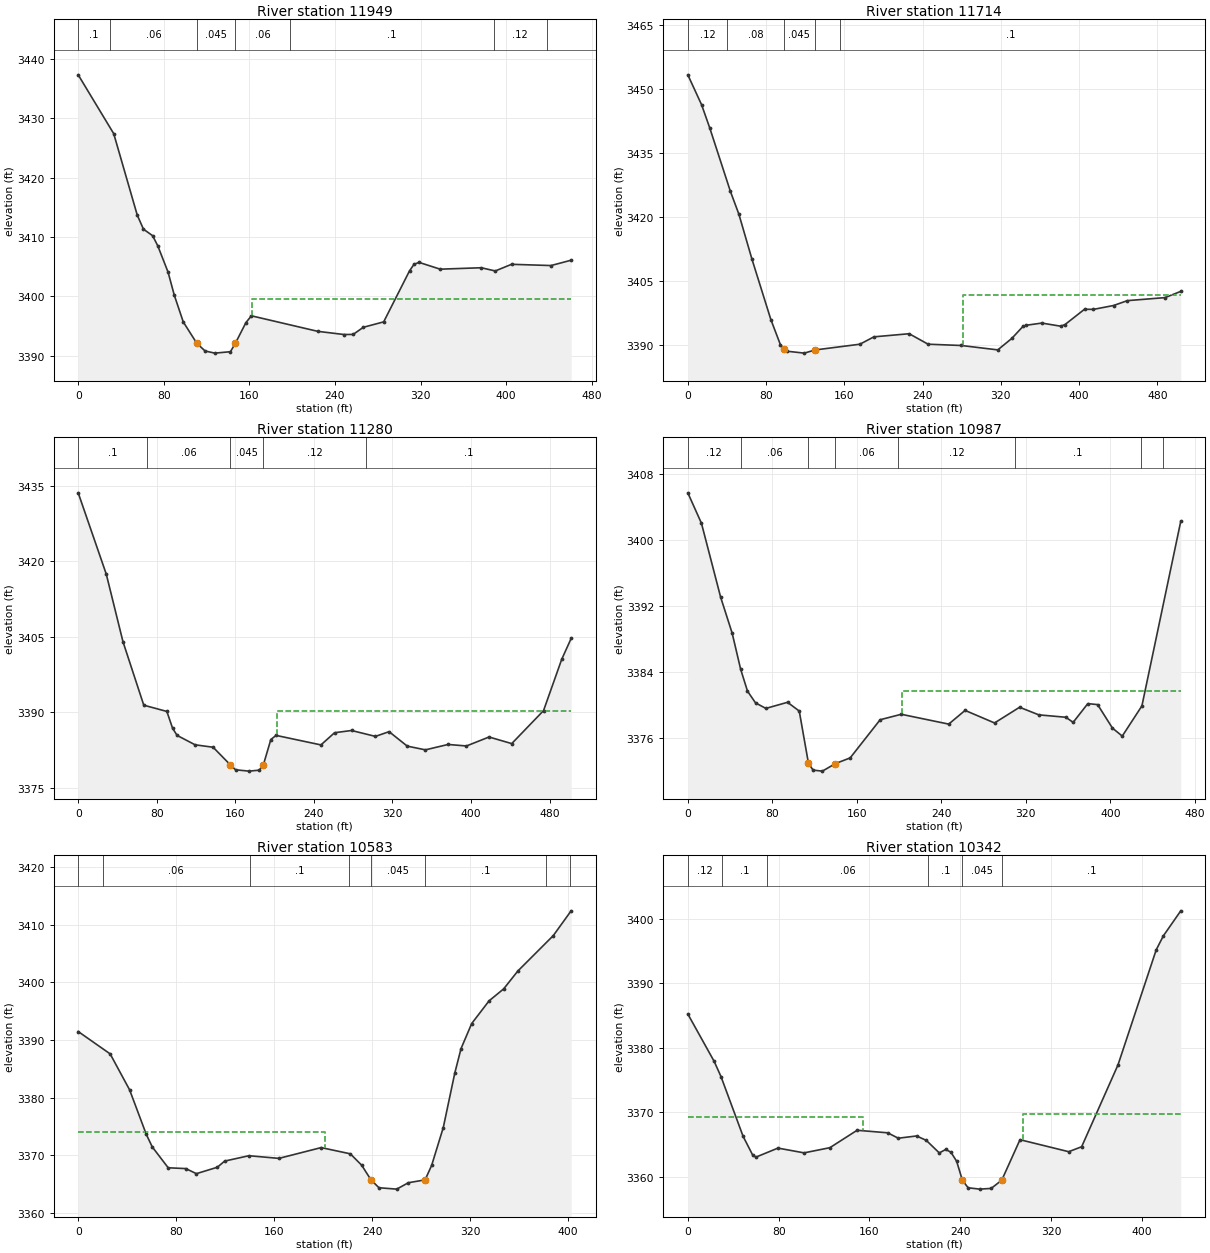
Type RM Length L Ch R = 1 ,11949   ,240.9,235.1,226
XS GIS Cut Line= 4
2170310.03896609460282.9032264262170350.02525969460344.132238506
 2170415.0029868460439.0996858132170561.20287278460669.020874031
#Sta/Elev= 30
       0  3437.3    33.2  3427.4    55.2 3413.69      61 3411.32    69.6 3410.22
    74.4 3408.51      84 3404.09    89.8 3400.22    98.2 3395.71   110.93392.105
   118.6 3390.82   127.7 3390.46   142.3  3390.7  146.863392.106   156.8 3395.61
   161.9 3396.74   223.8 3394.13   248.5 3393.59     257 3393.61   266.5 3394.81
   285.5 3395.72   309.7 3404.32   313.9 3405.42   318.6 3405.73   338.3 3404.59
   376.7 3404.83   389.8 3404.29     405 3405.41   441.9  3405.2   460.7  3406.1
#Mann= 7 ,-1,0
       0      .1       0      30     .06       0   110.9    .045       0
  146.86     .06       0   198.2      .1       0   388.2     .12       0
   438.2      .1       0
#XS Ineff= 2 , 0
                          162.82         3399.55
Permanent Ineff=
       F       F
Bank Sta=110.9,146.86
XS Rating Curve= 0 ,0
Exp/Cntr(USF)=0,0
Exp/Cntr=0.3,0.1

Type RM Length L Ch R = 1 ,11714   ,432.4,434.1,428.6
XS GIS Cut Line= 4
2170100.11092467460461.5919759652170156.34165005460495.330411192
2170272.55181584460576.5525700732170517.46786416460743.995174536
#Sta/Elev= 30
       0 3453.35    14.1 3446.32    22.5 3440.84    43.5 3426.04    52.2 3420.67
    65.6  3410.1    84.9 3395.95    94.7 3390.04    98.13389.052   101.3 3388.53
   119.1 3388.08     130 3388.82   175.9 3390.17   190.3  3391.9   226.3 3392.63
   245.7 3390.17   279.6 3389.87   316.9 3388.84   331.3 3391.54   342.6 3394.33
   345.7 3394.61     362 3395.13   381.3 3394.39   385.7 3394.79   405.6 3398.37
   414.7 3398.34   435.3 3399.25   449.4 3400.39   487.9  3401.1     504 3402.56
#Mann= 5 ,-1,0
       0     .12       0      40     .08       0    98.1    .045       0
     130     .08       0  155.58      .1       0
#XS Ineff= 2 , 0
                          281.06         3401.66
Permanent Ineff=
       F       F
Bank Sta=98.1,130
XS Rating Curve= 0 ,0
Exp/Cntr(USF)=0,0
Exp/Cntr=0.3,0.1

Type RM Length L Ch R = 1 ,11280   ,292.8,293.2,290.9
XS GIS Cut Line= 4
2169976.40332884460853.9574819452170076.36906285460910.188207324
2170197.57751533460977.6650777792170412.50384345461102.622245289
#Sta/Elev= 30
       0 3433.56    28.6 3417.43    45.6 3404.03    66.8 3391.43    90.3 3390.19
    96.1 3386.87   100.7 3385.44   119.1 3383.57   137.4 3383.09  155.073379.569
   160.3 3378.61     174 3378.35   184.4 3378.54  188.53 3379.57   196.2 3384.62
   201.5 3385.44   247.2 3383.55   261.1 3385.97   278.4 3386.41   302.7 3385.24
   316.6 3386.18   335.1 3383.31   353.6 3382.57   376.7 3383.64   395.4 3383.34
   418.4 3385.12   441.5 3383.81   473.9 3390.36   492.4 3400.53     502 3404.67
#Mann= 5 ,-1,0
       0      .1       0      70     .06       0  155.07    .045       0
  188.53     .12       0  293.42      .1       0
#XS Ineff= 2 , 0
                          201.98         3390.26
Permanent Ineff=
       F       F
Bank Sta=155.07,188.53
XS Rating Curve= 0 ,0
Exp/Cntr(USF)=0,0
Exp/Cntr=0.3,0.1

Type RM Length L Ch R = 1 ,10987   ,397,403.6,409.9
XS GIS Cut Line= 4
2169857.69401971461113.8683903652169936.41703524461162.601685693
2170033.88362589461206.3366943222170263.80481411461342.540006907
#Sta/Elev= 30
       0 3405.71    12.9 3402.03    31.1 3393.07      42 3388.72      50 3384.37
    56.5 3381.71    64.1 3380.29    73.9 3379.62    94.4 3380.36   105.5  3379.3
   114.2 3372.99   118.6 3372.15   127.4 3372.03   139.7 3372.94   153.7 3373.63
   182.1 3378.25   202.1 3378.91     247 3377.72   262.5 3379.38   290.4 3377.86
   314.1 3379.76   332.3 3378.84   357.9 3378.55   364.8 3377.93   378.7  3380.2
     388 3380.08     402 3377.24   411.3 3376.27   429.9 3379.92   466.7 3402.27
#Mann= 8 ,-1,0
       0     .12       0      50     .06       0   114.2    .045       0
   139.7     .06       0  199.42     .12       0  309.42      .1       0
  429.42     .12       0  449.42      .1       0
#XS Ineff= 2 , 0
                          202.42          3381.7
Permanent Ineff=
       F       F
Bank Sta=114.2,139.7
XS Rating Curve= 0 ,0
Exp/Cntr(USF)=0,0
Exp/Cntr=0.3,0.1

Type RM Length L Ch R = 1 ,10583   ,238.4,241.2,242.9
XS GIS Cut Line= 4
2169718.99156377461403.7690189872169882.68545321461521.228756446
2169992.64776062461591.2047702512170052.62720102461628.691920504
#Sta/Elev= 30
       0 3391.49    26.1 3387.61      42 3381.37    55.6 3373.66    60.5 3371.48
    73.5 3367.87    87.9 3367.73    96.5 3366.85   113.6 3367.96   119.6 3369.03
   139.4 3369.96   163.9  3369.5   198.4 3371.37   222.2 3370.29   231.5 3368.31
  239.053365.778   245.6 3364.41   260.1 3364.17   269.6 3365.28  283.253365.776
   288.6 3368.28   298.1 3374.84   307.5 3384.29   312.6 3388.53   321.3 3392.87
   335.5 3396.81   347.4 3398.88     359 3401.98   387.9 3408.11   402.5 3412.41
#Mann= 8 ,-1,0
       0      .1       0      20     .06       0     140      .1       0
  221.48     .06       0  239.05    .045       0  283.25      .1       0
  381.82     .12       0  401.82      .1       0
#XS Ineff= 2 , 0
          201.32 3374.09
Permanent Ineff=
       F       F
Bank Sta=239.05,283.25
XS Rating Curve= 0 ,0
Exp/Cntr(USF)=0,0
Exp/Cntr=0.3,0.1

Type RM Length L Ch R = 1 ,10342   ,241,246.1,250.8
XS GIS Cut Line= 4
2169615.27711474461581.208196851  2169752.729999461714.912366086
2169850.19658965461791.1362382672169945.16403696461862.361823747
#Sta/Elev= 30
       0 3385.22    23.2 3377.88    29.2 3375.53    48.7 3366.26    57.1 3363.37
      60 3363.04    79.4 3364.44   102.4  3363.7   125.1  3364.5   149.1  3367.2
     176 3366.81   185.4 3365.97   201.5 3366.32   210.1 3365.63   221.5 3363.69
   227.2 3364.23   231.7 3363.81   236.8  3362.4   241.8 3359.47   246.9 3358.29
   257.1 3358.08   267.2 3358.19  276.533359.469   292.6 3365.74   335.5 3363.88
   346.9 3364.65   378.9 3377.33   412.6 3395.18   418.9 3397.34   434.2 3401.21
#Mann= 6 ,-1,0
       0     .12       0      30      .1       0      70     .06       0
  211.76      .1       0   241.8    .045       0  276.53      .1       0
#XS Ineff= 2 , 0
          154.57 3369.27  294.83         3369.73
Permanent Ineff=
       F       F
Bank Sta=241.8,276.53
XS Rating Curve= 0 ,0
Exp/Cntr(USF)=0,0
Exp/Cntr=0.3,0.1

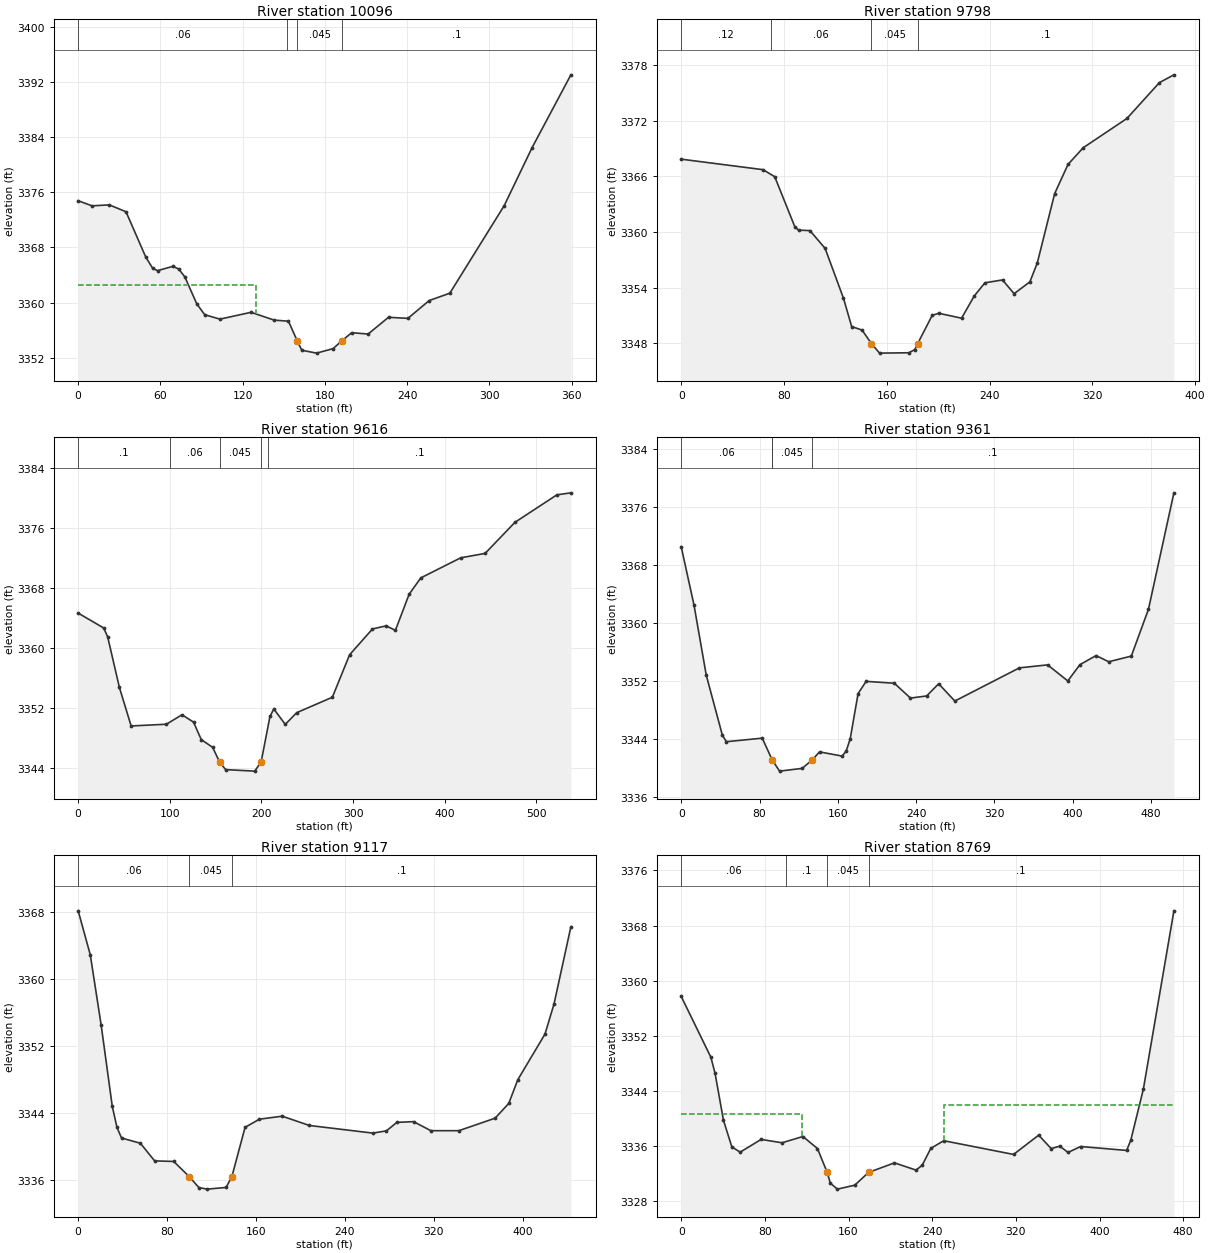
Type RM Length L Ch R = 1 ,10096   ,293.5,297.6,301.4
XS GIS Cut Line= 4
2169537.80367088461806.1310983682169615.27711474461901.098545675
2169695.24970194462001.064279683 2169767.7248591462082.286438564
#Sta/Elev= 30
       0 3374.76    10.1 3374.02    22.7 3374.16    34.9 3373.16    49.3 3366.59
    54.4 3364.94    57.9 3364.62    69.2 3365.25    73.4 3364.84    77.8 3363.72
    86.5 3359.81    92.3 3358.23   103.4 3357.59   126.1 3358.58   142.9 3357.45
   153.4 3357.29  159.733354.465   163.1 3353.08   173.9 3352.66   185.9 3353.31
  192.453354.463   199.5 3355.62   211.5 3355.43   226.4 3357.86   240.5  3357.7
   256.1 3360.29   271.1 3361.35   310.8 3374.06   331.1 3382.46   359.4 3393.02
#Mann= 4 ,-1,0
       0     .06       0  152.56      .1       0  159.73    .045       0
  192.45      .1       0
#XS Ineff= 2 , 0
          129.81 3362.58
Permanent Ineff=
       F       F
Bank Sta=159.73,192.45
XS Rating Curve= 0 ,0
Exp/Cntr(USF)=0,0
Exp/Cntr=0.3,0.1

Type RM Length L Ch R = 1 ,9798    ,176.4,182.3,188.2
XS GIS Cut Line= 4
2169329.12520114461964.8267011052169386.60549819462073.539436839
2169447.83451027462186.0008875972169509.06352235462303.460625056
#Sta/Elev= 30
       0 3367.84    63.7 3366.71    72.8 3365.95    88.4 3360.58    91.3  3360.2
   100.2 3360.15     112 3358.24   126.3 3352.87   132.7 3349.82   140.8 3349.44
  148.053347.987   154.4 3346.96   177.2    3347   181.8 3347.34  184.063347.988
   195.4 3351.03   200.5 3351.25   218.2 3350.72   228.1 3353.11   236.4 3354.53
   250.1 3354.84   259.1 3353.36   271.4 3354.63   277.2 3356.68   290.7 3364.14
   301.1 3367.28   312.9 3369.07   346.9 3372.22   372.2 3376.08   383.5 3376.92
#Mann= 4 ,-1,0
       0     .12       0      70     .06       0  148.05    .045       0
  184.06      .1       0
Bank Sta=148.05,184.06
XS Rating Curve= 0 ,0
Exp/Cntr(USF)=0,0
Exp/Cntr=0.3,0.1

Type RM Length L Ch R = 1 ,9616    ,252,255.1,256.7
XS GIS Cut Line= 4
2169189.17317353462031.0539998852169230.40903881462141.016307294
2169267.89618906462268.4726181542169440.33708022462498.393806371
#Sta/Elev= 30
       0 3364.67    27.9 3362.68    32.2  3361.5      45 3354.77    57.8 3349.65
    96.3 3349.88   113.3 3351.14   125.9 3350.16   134.3 3347.84   146.8  3346.8
  154.243344.866   160.9 3343.84   192.7 3343.64  199.683344.866   209.3 3350.91
   213.5 3351.91     226 3349.86   238.5 3351.42   277.4 3353.47   296.2 3359.12
   321.2 3362.56   336.2 3362.97   346.2 3362.37   361.2 3367.18   373.9 3369.35
   417.4 3372.02   444.1 3372.61   476.7 3376.75   522.4  3380.4   537.7 3380.67
#Mann= 5 ,-1,0
       0      .1       0     100     .06       0  154.24    .045       0
  199.68     .06       0  207.44      .1       0
Bank Sta=154.24,199.68
XS Rating Curve= 0 ,0
Exp/Cntr(USF)=0,0
Exp/Cntr=0.3,0.1

Type RM Length L Ch R = 1 ,9361    ,247.7,244.2,238.8
XS GIS Cut Line= 4
2168976.74598876462128.5205905432168985.49299049 462159.75988242
2169016.73228237462315.9563418072169091.70658287462618.352687181
#Sta/Elev= 30
       0 3370.51    13.1 3362.46    25.6 3352.82      42 3344.58    46.1 3343.66
    82.8 3344.15   92.823341.184   100.5 3339.61   123.6 3339.99  134.053341.183
   141.3 3342.26   164.4 3341.68   168.5 3342.37   172.6 3344.03   180.7 3350.29
   188.9 3351.97   217.7 3351.71   234.2 3349.67   250.7 3349.96     263 3351.64
   279.5 3349.26   345.5 3353.83   374.3 3354.24   394.9 3352.03   407.3 3354.27
   423.8 3355.52   436.7 3354.67   459.8 3355.45   477.3 3361.89   503.3 3377.93
#Mann= 4 ,-1,0
       0     .06       0   92.44      .1       0   92.82    .045       0
  134.05      .1       0
Bank Sta=92.82,134.05
XS Rating Curve= 0 ,0
Exp/Cntr(USF)=0,0
Exp/Cntr=0.3,0.1

Type RM Length L Ch R = 1 ,9117    ,346.6,347.5,339.3
XS GIS Cut Line= 4
2168740.57694217 462223.488037852168751.82308725462265.973474803
2168795.55809587462379.684497237 2168849.2896779462652.091122408
#Sta/Elev= 30
       0  3368.1    10.9 3362.85    20.7 3354.46    30.7 3344.77    34.9 3342.28
      39 3341.01      56 3340.38    68.8 3338.28      86 3338.21   99.993336.396
   108.6  3335.1     116 3334.91   133.1 3335.11  138.313336.394   150.2 3342.28
   163.1 3343.25   183.6 3343.61   208.1  3342.5   265.2 3341.59   277.4 3341.86
   286.8 3342.87   301.8 3342.96   317.4 3341.88   342.6 3341.88   375.2 3343.37
   387.5 3345.13   395.6 3347.95   420.1  3353.4   428.2 3356.97   443.4  3366.2
#Mann= 3 ,-1,0
       0     .06       0   99.99    .045       0  138.31      .1       0
Bank Sta=99.99,138.31
XS Rating Curve= 0 ,0
Exp/Cntr(USF)=0,0
Exp/Cntr=0.3,0.1

Type RM Length L Ch R = 1 ,8769    ,237,250.9,271.2
XS GIS Cut Line= 4
2168425.68488005462224.7376095252168424.43530837462349.694777035
2168491.91217883462472.152801194 2168498.1600372462678.332127585
#Sta/Elev= 30
       0 3357.73    28.4  3348.9    32.4 3346.56    40.4 3339.78    48.4 3335.92
    56.4 3335.15    76.4    3337    96.4 3336.51   116.4 3337.42   130.3 3335.67
   139.63332.208   142.6 3330.66   149.3 3329.79   165.9 3330.36  179.113332.207
   203.9  3333.6   224.5 3332.55   230.4 3333.24   238.6 3335.69     251 3336.81
   317.8 3334.82   341.8 3337.62   353.8 3335.66   361.9 3336.02   369.9 3335.11
   381.9 3335.97   425.9  3335.4   429.9 3336.89   441.9 3344.29   471.1 3370.14
#Mann= 4 ,-1,0
       0     .06       0     100      .1       0   139.6    .045       0
  179.11      .1       0
#XS Ineff= 2 , 0
          115.51 3340.64  250.83            3342
Permanent Ineff=
       F       F
Bank Sta=139.6,179.11
XS Rating Curve= 0 ,0
Exp/Cntr(USF)=0,0
Exp/Cntr=0.3,0.1

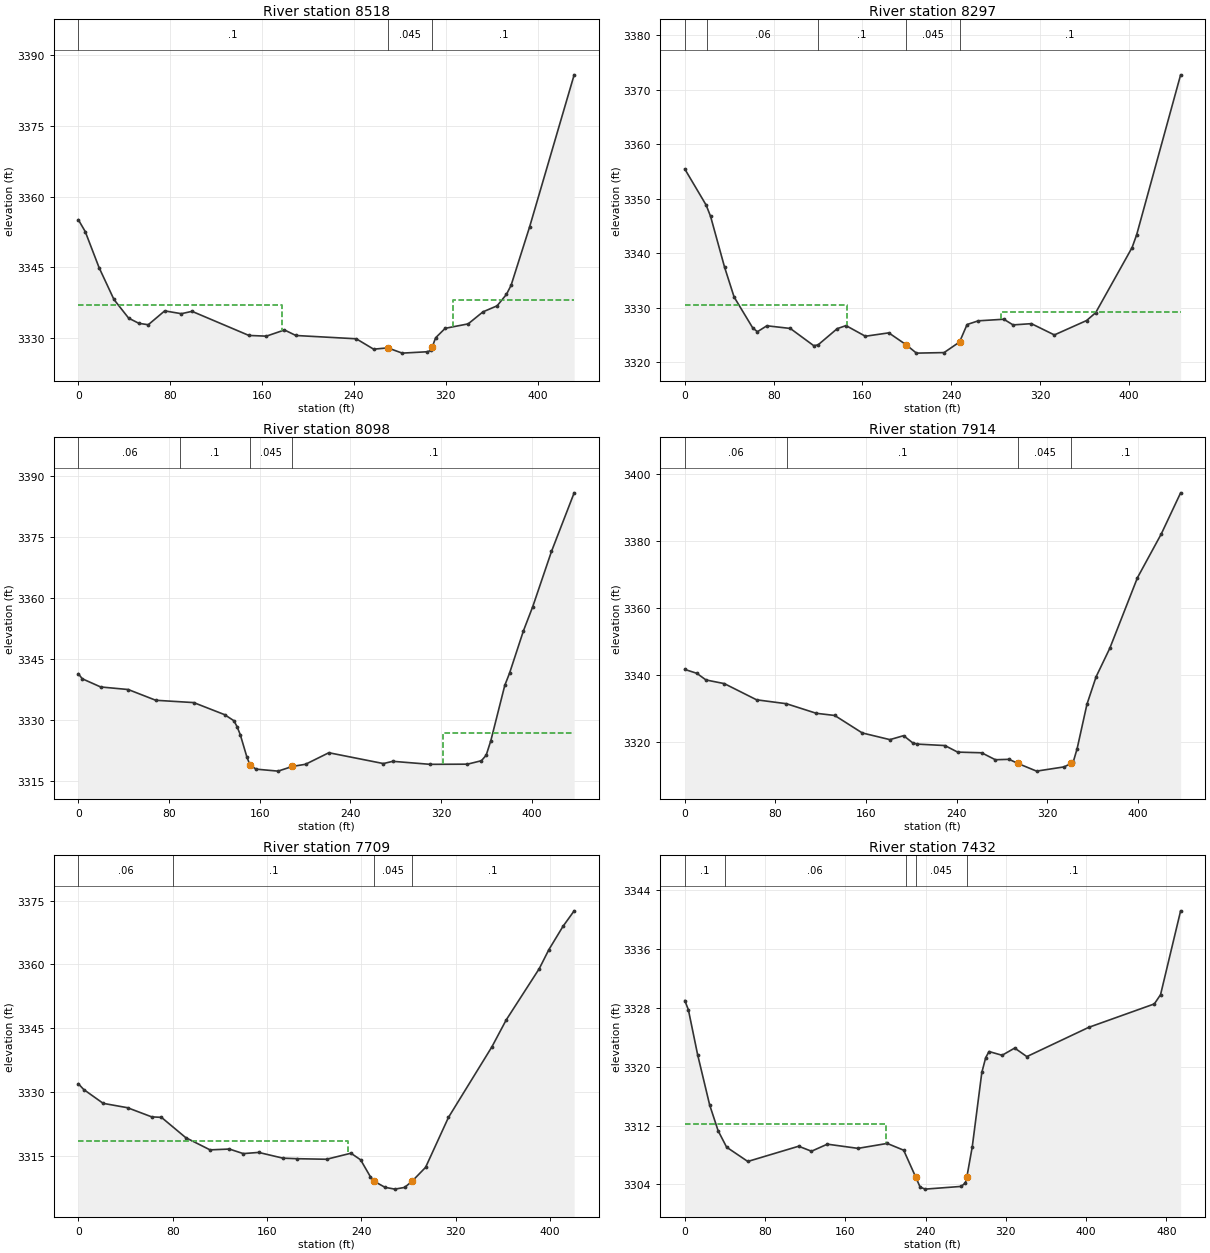
Type RM Length L Ch R = 1 ,8518    ,222.4,221.3,220.8
XS GIS Cut Line= 4
2168346.96186451462232.2350395762168264.49013396462448.410939367
2168234.50041376462555.8741034262168249.49527386462643.344120682
#Sta/Elev= 30
       0 3355.12       6 3352.61    18.1 3344.94      31 3338.21    43.8 3334.25
    52.7 3333.15    60.9 3332.85    75.2 3335.79    89.7 3335.19      99 3335.69
   148.5 3330.58   163.7 3330.43   179.5 3331.74   189.4 3330.57     242 3329.87
   257.1 3327.67   269.5 3327.94     282 3326.83   303.7 3327.12     307 3327.39
  308.273328.223   311.1 3330.09   319.4 3332.09   339.4 3333.03   352.3 3335.58
   364.6 3336.86   372.7 3339.27   376.8 3341.22     393 3353.67   431.7 3385.84
#Mann= 3 ,-1,0
       0      .1       0   269.5    .045       0  308.27      .1       0
#XS Ineff= 2 , 0
          177.67 3337.08  326.18         3338.03
Permanent Ineff=
       F       F
Bank Sta=269.5,308.27
XS Rating Curve= 0 ,0
Exp/Cntr(USF)=0,0
Exp/Cntr=0.3,0.1

Type RM Length L Ch R = 1 ,8297    ,219.9,198.6,178
XS GIS Cut Line= 4
2168114.54153295462207.2436060742168054.56209254462383.433212262
2168010.82708391  462547.12710172168030.82023072462635.846690632
#Sta/Elev= 30
       0 3355.47    19.2 3348.86    23.2 3346.79    35.8 3337.47    44.4 3331.98
    61.2  3326.3    65.4 3325.61    73.9  3326.7      95 3326.21   116.1 3323.05
     120 3323.19   137.3 3326.18   145.2 3326.73   162.6 3324.78   183.7  3325.4
   199.3 3323.22   208.6 3321.68   233.5 3321.78   247.4 3323.72   254.2 3326.93
   264.3 3327.61   287.3  3327.9   295.6 3326.86   312.1 3327.09   332.8 3325.02
   361.8 3327.66     370  3329.1   402.8 3341.06   406.9  3343.4   446.5 3372.76
#Mann= 5 ,-1,0
       0      .1       0      20     .06       0     120      .1       0
   199.3    .045       0   247.4      .1       0
#XS Ineff= 2 , 0
          145.76 3330.45  284.42         3329.18
Permanent Ineff=
       F       F
Bank Sta=199.3,247.4
XS Rating Curve= 0 ,0
Exp/Cntr(USF)=0,0
Exp/Cntr=0.3,0.1

Type RM Length L Ch R = 1 ,8098    ,162.8,184,191.9
XS GIS Cut Line= 4
2167857.12976788462229.735896226 2167835.8870494462364.689637136
2167882.12120138462430.9169359162167934.60321173462644.593692357
#Sta/Elev= 30
       0 3341.38     3.5 3340.14    19.7 3338.13      44  3337.5    68.3 3334.86
   101.8 3334.29     129 3331.33   137.2 3329.84     140  3328.4   142.9 3326.37
   148.7 3320.91  151.383319.005   156.7 3317.94   176.2 3317.45   188.9 3318.61
   200.4 3319.13     221 3321.97   269.1 3319.31   277.4 3319.86   310.3 3319.12
   343.3 3319.16   355.6 3320.01   359.8 3321.37   363.9 3324.94   376.2 3338.52
   380.4 3341.52   392.7 3351.96   400.9 3357.89   417.4 3371.43   437.4 3385.83
#Mann= 4 ,-1,0
       0     .06       0      90      .1       0  151.38    .045       0
   188.9      .1       0
#XS Ineff= 2 , 0
                          321.88         3326.87
Permanent Ineff=
       F       F
Bank Sta=151.38,188.9
XS Rating Curve= 0 ,0
Exp/Cntr(USF)=0,0
Exp/Cntr=0.3,0.1

Type RM Length L Ch R = 1 ,7914    ,192.1,205.7,214.3
XS GIS Cut Line= 4
2167793.40161245462234.7341829262167757.16403387462445.911796017
2167778.40675235462587.1133953032167789.65289742462667.085982509
#Sta/Elev= 30
       0 3341.74    10.6 3340.59    18.7 3338.61    34.9 3337.52    63.4  3332.7
    89.7 3331.54   116.1 3328.69   132.4 3328.04   156.7 3322.84   181.1 3320.85
   193.2 3322.03   201.3 3319.88   205.4 3319.52   229.7 3319.09   240.9 3317.14
   262.1 3316.94   274.2 3314.87   286.3 3314.99  294.143313.765   310.6 3311.48
   334.9 3312.74  341.113313.767     343 3314.23   346.4 3318.14   355.1 3331.39
   363.2 3339.58   375.3 3348.07   399.7 3369.05   420.7 3382.05   437.8 3394.29
#Mann= 4 ,-1,0
       0     .06       0      90      .1       0  294.14    .045       0
  341.11      .1       0
Bank Sta=294.14,341.11
XS Rating Curve= 0 ,0
Exp/Cntr(USF)=0,0
Exp/Cntr=0.3,0.1

Type RM Length L Ch R = 1 ,7709    ,277,276.2,275.9
XS GIS Cut Line= 4
2167640.95386808462244.7307563272167588.47185773462458.407512768
 2167559.7317092462567.120248501 2167549.7351358462654.590265758
#Sta/Elev= 30
       0 3331.96     4.6  3330.6    21.1 3327.35    41.7 3326.33    62.2 3324.18
    70.5 3324.06    91.1 3319.29   111.7 3316.42   128.1 3316.61   139.9 3315.54
   152.9 3315.82   173.5 3314.47   185.8 3314.34   210.5 3314.21   231.2 3315.63
   239.4 3314.08   247.7  3310.1  251.053309.013   260.1 3307.61   268.4 3307.19
   276.7 3307.59  282.933309.013   294.5 3312.31   313.9 3324.05   350.7 3340.62
   362.8 3346.93   390.9 3359.02     399 3363.46     411 3368.95   420.5 3372.61
#Mann= 4 ,-1,0
       0     .06       0      80      .1       0  251.05    .045       0
  282.93      .1       0
#XS Ineff= 2 , 0
          228.82 3318.55
Permanent Ineff=
       F       F
Bank Sta=251.05,282.93
XS Rating Curve= 0 ,0
Exp/Cntr(USF)=0,0
Exp/Cntr=0.3,0.1

Type RM Length L Ch R = 1 ,7432    ,272.8,282.5,291.7
XS GIS Cut Line= 5
2167381.04295966462209.7427494242167319.81394759462389.681070638
2167289.82422738462524.6348115482167276.07893896462619.602258856
2167321.06351926462673.333840885
#Sta/Elev= 30
       0 3328.99     3.6 3327.72    12.8 3321.62    24.8 3314.79    33.2  3311.3
    41.7 3309.06    62.8 3307.12   113.5 3309.19   126.3 3308.51   142.1 3309.47
   172.6  3308.9   201.8 3309.57   218.2 3308.65     2303305.061   234.6 3303.64
   239.6 3303.36   275.6 3303.73   279.7 3304.21  281.263305.061   286.6 3309.13
   296.1 3319.21     300 3321.24   303.3 3322.06   316.3 3321.55   328.9 3322.53
     341 3321.37   402.6 3325.34   468.1 3328.53   474.3 3329.79   494.3 3341.18
#Mann= 5 ,-1,0
       0      .1       0      40     .06       0  220.07      .1       0
     230    .045       0  281.26      .1       0
#XS Ineff= 2 , 0
          200.77 3312.27
Permanent Ineff=
       F       F
Bank Sta=230,281.26
XS Rating Curve= 0 ,0
Exp/Cntr(USF)=0,0
Exp/Cntr=0.3,0.1

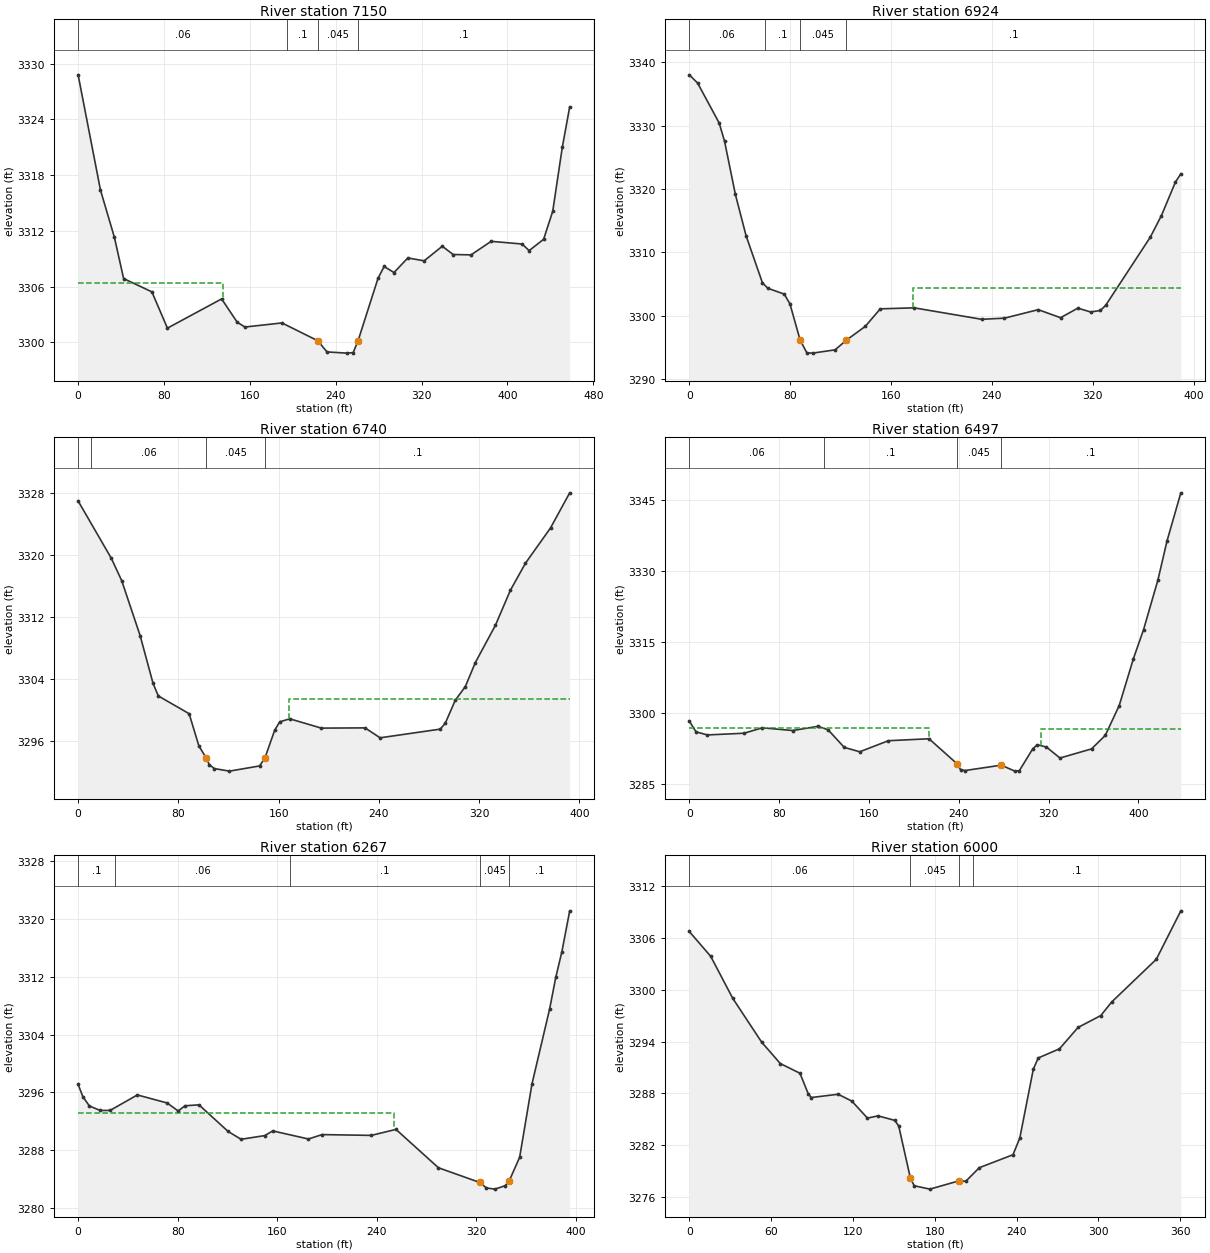
Type RM Length L Ch R = 1 ,7150    ,223.1,225.6,218.1
XS GIS Cut Line= 4
2167171.11491825462146.0145939942167146.12348475462205.994034399
2167013.66888719462405.9255024142166919.95101155462527.133954898
#Sta/Elev= 30
       0 3328.81    20.8 3316.41    33.8 3311.31    42.4 3306.87    68.7 3305.44
    83.2 3301.53   133.7 3304.68   148.2 3302.17   155.4 3301.65   189.9 3302.09
   223.23300.181   231.9 3298.97   250.5 3298.84   256.3  3298.9  260.853300.181
   279.4 3306.89   285.1 3308.17   294.3 3307.52   307.2 3309.09   322.4 3308.78
   339.3 3310.35   349.4 3309.46   366.1 3309.42   384.8 3310.88   413.7 3310.59
   420.2 3309.88   433.7  3311.1   442.2 3314.12   451.1    3321     458 3325.36
#Mann= 4 ,-1,0
       0     .06       0  194.98      .1       0   223.2    .045       0
  260.85      .1       0
#XS Ineff= 2 , 0
          135.31 3306.35
Permanent Ineff=
       F       F
Bank Sta=223.2,260.85
XS Rating Curve= 0 ,0
Exp/Cntr(USF)=0,0
Exp/Cntr=0.3,0.1

Type RM Length L Ch R = 1 ,6924    ,191.7,184.6,173.2
XS GIS Cut Line= 4
2166969.93387856462071.0402934882166944.94244506462136.018020593
2166818.73570587462387.1819272882166798.74255907462420.920362515
#Sta/Elev= 30
       0    3338     6.6 3336.71    23.7 3330.41      28 3327.51    36.6 3319.11
    45.1 3312.58      58 3305.19    62.3 3304.31    75.4 3303.38    79.9 3301.82
   87.933296.132    93.3 3294.11    97.8 3294.07   115.7 3294.59  124.713296.132
   139.6 3298.29   151.5 3301.06   178.4 3301.22   231.9 3299.41     250 3299.59
   276.8 3300.93   294.5 3299.66   308.2 3301.17   318.3 3300.57   326.1  3300.8
   330.3 3301.62   365.7 3312.38   374.5 3315.78   385.6 3321.07   389.9 3322.38
#Mann= 4 ,-1,0
       0     .06       0      60      .1       0   87.93    .045       0
  124.71      .1       0
#XS Ineff= 2 , 0
                          177.34         3304.32
Permanent Ineff=
       F       F
Bank Sta=87.93,124.71
XS Rating Curve= 0 ,0
Exp/Cntr(USF)=0,0
Exp/Cntr=0.3,0.1

Type RM Length L Ch R = 1 ,6740    ,247.6,242.4,237.7
XS GIS Cut Line= 4
2166776.25026892462019.8078548092166753.75797877 462096.03172699
2166746.26054872462189.7496026222166753.75797877462408.424645764
#Sta/Elev= 30
       0    3327    26.5  3319.6    34.8 3316.71    49.5 3309.62    59.8 3303.46
      64 3301.84    88.6 3299.55    96.4 3295.38  102.28 3293.82   104.7 3292.97
   108.7 3292.47   120.8 3292.14   144.8 3292.81  149.03 3293.82   156.9 3297.43
   160.9  3298.5   168.9 3298.89   194.1 3297.69     229 3297.72     241 3296.44
     289 3297.56     293 3298.32     301 3301.29     309 3303.05     317 3306.15
     333 3310.95     345 3315.49     357 3318.97     377 3323.52   392.3 3328.05
#Mann= 4 ,-1,0
       0      .1       0      10     .06       0  102.28    .045       0
  149.03      .1       0
#XS Ineff= 2 , 0
                           168.1         3301.39
Permanent Ineff=
       F       F
Bank Sta=102.28,149.03
XS Rating Curve= 0 ,0
Exp/Cntr(USF)=0,0
Exp/Cntr=0.3,0.1

Type RM Length L Ch R = 1 ,6497    ,213.7,230.1,248.1
XS GIS Cut Line= 4
2166580.06751593461924.8404075022166500.09492872462067.291578463
 2166521.3376472462283.4674782552166498.84535705462335.949488609
#Sta/Elev= 30
       0 3298.35       6 3296.05    16.1 3295.39    48.8 3295.75    65.1  3296.9
    92.1 3296.32   114.7 3297.21   123.6 3296.48     138 3292.76   151.8 3291.83
   177.3 3294.17   213.5 3294.58   238.4  3289.3   241.6 3288.05   245.6 3287.87
   277.8    3289   289.9 3287.74   293.9 3287.83   305.9 3292.48     310 3293.32
     318 3292.83   330.1 3290.51   358.2 3292.44   370.4 3295.29   382.8 3301.58
   395.5 3311.53   404.5 3317.63   417.3 3328.14   425.4 3336.39   437.7 3346.56
#Mann= 4 ,-1,0
       0     .06       0     120      .1       0   238.4    .045       0
   277.8      .1       0
#XS Ineff= 2 , 0
          213.42 3296.76  313.53         3296.55
Permanent Ineff=
       F       F
Bank Sta=238.4,277.8
XS Rating Curve= 0 ,0
Exp/Cntr(USF)=0,0
Exp/Cntr=0.3,0.1

Type RM Length L Ch R = 1 ,6267    ,266.3,267.4,264.4
XS GIS Cut Line= 4
 2166526.3359339 461902.348117352166356.39418609462084.785581914
2166261.42673878462164.7581691212166248.93102203462182.252172572
#Sta/Elev= 30
       0  3297.1     3.9 3295.39       9 3294.13    17.7  3293.5    25.7 3293.51
    47.6 3295.65    71.5 3294.54    80.4 3293.43    85.9 3294.15    97.1 3294.28
   120.5  3290.6   130.9 3289.51   149.9 3290.02   156.4 3290.67   185.1 3289.55
     196 3290.16   235.6 3290.05   255.4 3290.88   289.5 3285.57   322.8 3283.53
   328.1 3282.77   334.9 3282.61   343.1 3283.08   346.3 3283.71   354.8 3287.03
   364.7 3297.18   378.9 3307.57   383.8 3311.92   388.7 3315.46     395 3321.14
#Mann= 5 ,-1,0
       0      .1       0      30     .06       0     170      .1       0
   322.8    .045       0   346.3      .1       0
#XS Ineff= 2 , 0
          253.91 3293.18
Permanent Ineff=
       F       F
Bank Sta=322.8,346.3
XS Rating Curve= 0 ,0
Exp/Cntr(USF)=0,0
Exp/Cntr=0.3,0.1

Type RM Length L Ch R = 1 ,6000    ,218.7,220.6,218.2
XS GIS Cut Line= 4
2166357.64375776461794.8849532922166256.42845208461856.113965372
2166136.46957127461943.5839826282166110.22856609462033.553143235
#Sta/Elev= 30
       0 3306.74    15.7 3303.87    31.9    3299    53.1 3293.93    66.8 3291.45
    81.2 3290.33    87.2 3287.97    89.4 3287.52   109.2  3287.9   119.2 3287.11
   130.7 3285.14   138.4  3285.4   150.7 3284.88   153.6 3284.23   162.2 3278.17
     165 3277.31   176.5 3276.92   197.8 3277.88   202.8 3277.83   212.7  3279.4
   237.4  3280.9   242.4 3282.83   252.3 3290.79   255.9  3292.1   271.5 3293.16
   285.1 3295.63   301.8 3297.01   309.8 3298.58   342.5 3303.52   360.5 3309.13
#Mann= 4 ,-1,0
       0     .06       0   162.2    .045       0   197.8     .06       0
  208.29      .1       0
Bank Sta=162.2,197.8
XS Rating Curve= 0 ,0
Exp/Cntr(USF)=0,0
Exp/Cntr=0.3,0.1