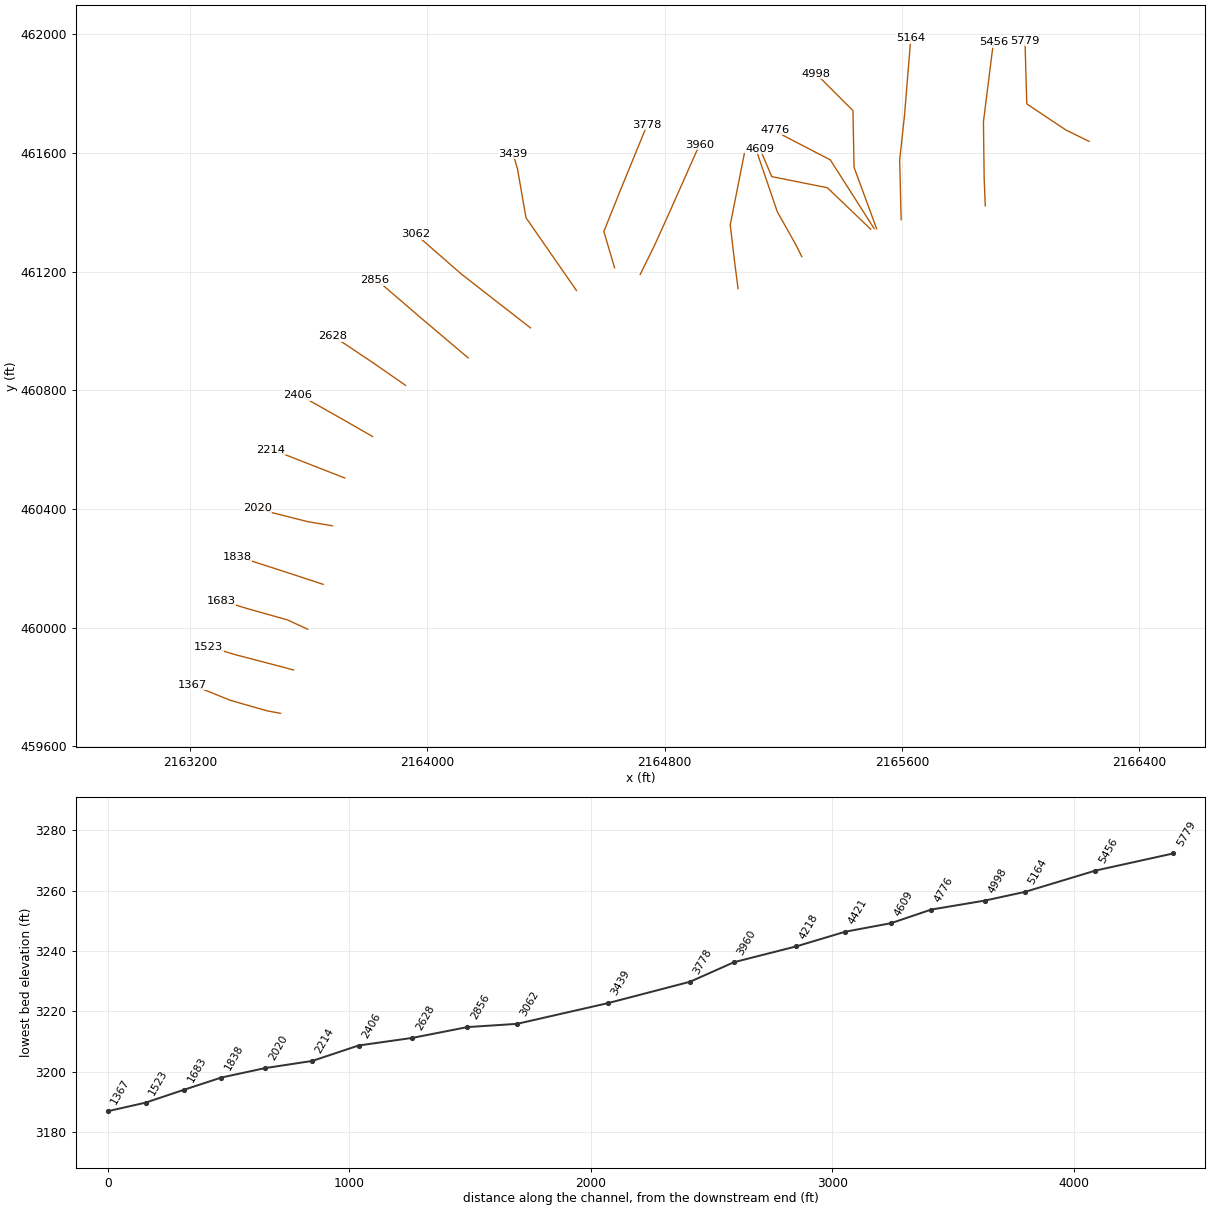
HEC-RAS study NFCRNBRYRV.prj: NFCRNBRYRV

--- NFCRNBRYRV.g01 (geometry) --- (continued)

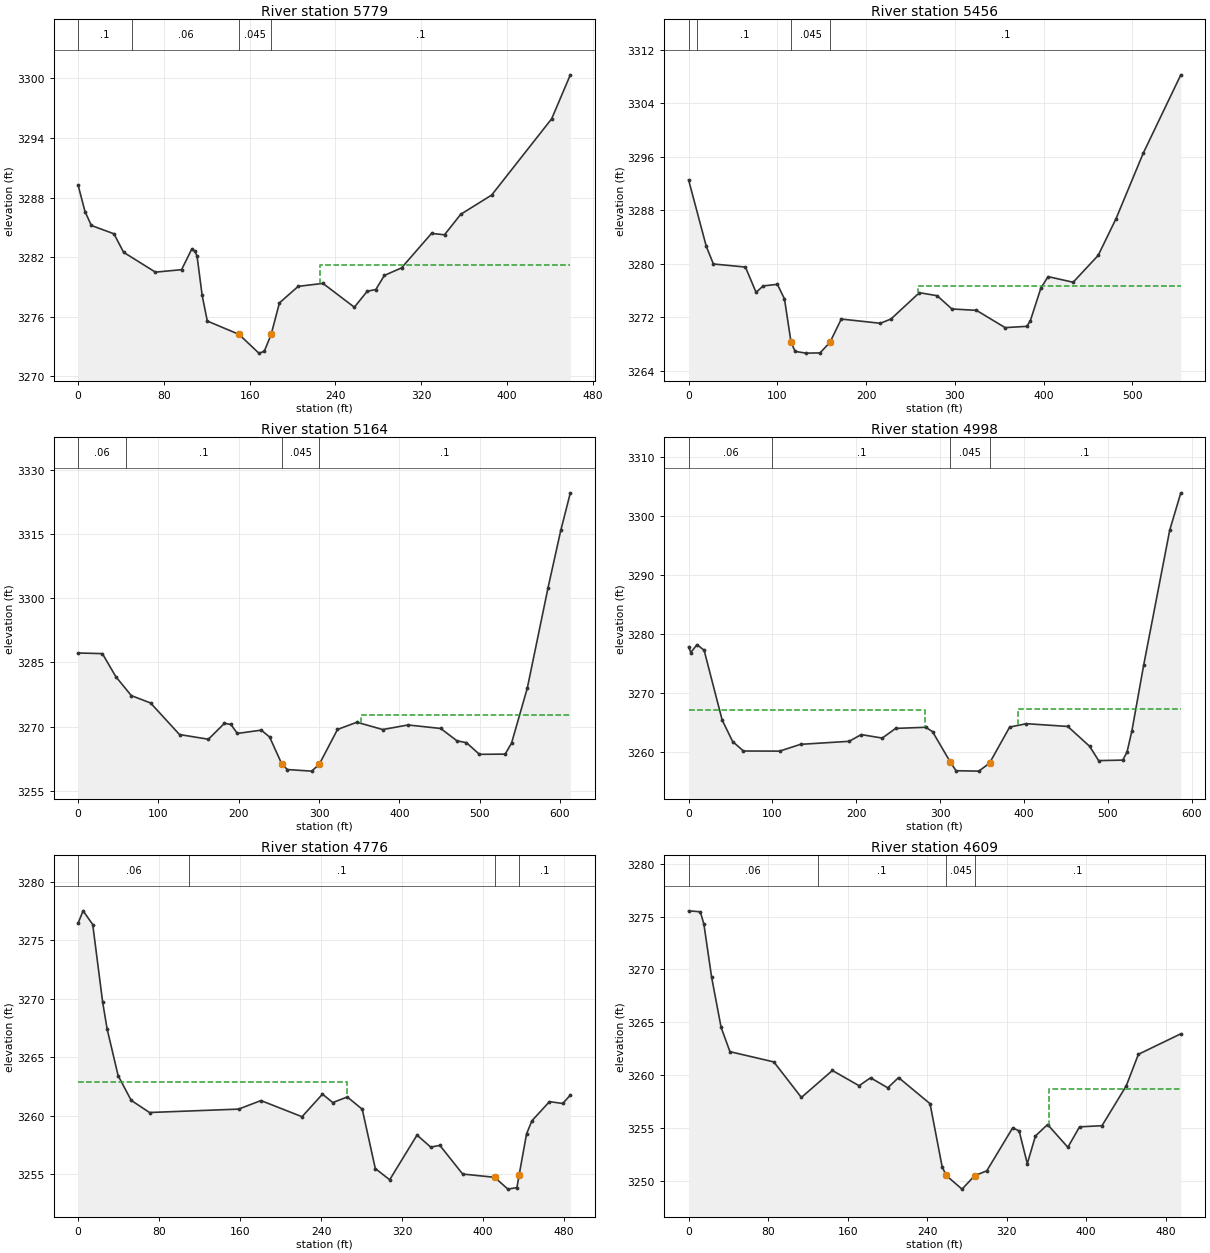
Type RM Length L Ch R = 1 ,5779    ,339.5,322.7,292.6
XS GIS Cut Line= 4
 2166230.1874469461638.6884939052166151.46443137461677.425215833
2166020.25940549 461764.895233092166014.01154711461978.571989531
#Sta/Elev= 30
       0 3289.23     6.4 3286.59    12.3 3285.19    33.4 3284.35    42.4 3282.49
    72.1 3280.49    96.5 3280.74   106.1 3282.84   108.9 3282.59   110.9 3282.13
   115.7 3278.15   120.5 3275.57  150.053274.228   168.6 3272.34   173.6 3272.51
  180.083274.228   187.8  3277.4   205.3 3279.06   228.4 3279.36   257.7 3276.96
   269.7 3278.57   277.7 3278.74   285.7 3280.16   301.7 3280.92   329.7 3284.39
   341.8 3284.25   356.9 3286.31   385.8 3288.25   441.8 3295.93   459.2 3300.35
#Mann= 4 ,-1,0
       0      .1       0      50     .06       0  150.05    .045       0
  180.08      .1       0
#XS Ineff= 2 , 0
                          225.52         3281.19
Permanent Ineff=
       F       F
Bank Sta=150.05,180.08
XS Rating Curve= 0 ,0
Exp/Cntr(USF)=0,0
Exp/Cntr=0.3,0.1

Type RM Length L Ch R = 1 ,5456    ,296.7,292.6,290.4
XS GIS Cut Line= 4
2165880.30737787461421.2630224382165876.55866285 461509.98261137
 2165874.0595195461704.9157926852165907.79795473461973.573702831
#Sta/Elev= 30
       0 3292.52    19.9 3282.61    27.9 3279.97      64 3279.51      76 3275.73
      84 3276.69     100 3276.93     108 3274.75  115.423268.252     120 3266.91
   132.2 3266.65     148 3266.68   159.23268.256     172 3271.74     216 3271.11
     228 3271.75     260 3275.68     280 3275.23   296.6 3273.25   324.3 3273.04
   356.6 3270.46   380.8 3270.65   384.8 3271.42   396.9 3276.38     405 3278.08
   433.2 3277.24   461.4 3281.25   481.6 3286.76   512.1  3296.5   554.5 3308.23
#Mann= 4 ,-1,0
       0     .06       0      10      .1       0  115.42    .045       0
   159.2      .1       0
#XS Ineff= 2 , 0
                          258.75         3276.74
Permanent Ineff=
       F       F
Bank Sta=115.42,159.2
XS Rating Curve= 0 ,0
Exp/Cntr(USF)=0,0
Exp/Cntr=0.3,0.1

Type RM Length L Ch R = 1 ,5164    ,162,166,169.1
XS GIS Cut Line= 4
2165596.65460763 461375.028870462165591.65632093 461576.20991015
 2165607.9007527461724.9089394872165629.14347118461986.069419582
#Sta/Elev= 30
       0 3287.22    30.2 3287.07    46.8 3281.71    66.2 3277.25    90.2 3275.52
   126.2 3268.14   162.2 3267.04   182.2 3270.78   190.2 3270.49   198.2  3268.4
     228 3269.17   238.4 3267.56  253.753261.166   260.6 3259.95   290.7 3259.58
  300.163261.166   322.9 3269.33   347.1 3271.02   379.2 3269.31   410.7 3270.38
   451.4 3269.56   471.5 3266.69   483.5 3266.23   499.6 3263.51   531.7 3263.56
   539.7 3266.19   559.2 3278.99   585.1 3302.54   600.9 3315.91   612.8 3324.69
#Mann= 4 ,-1,0
       0     .06       0      60      .1       0  253.75    .045       0
  300.16      .1       0
#XS Ineff= 2 , 0
                          351.93         3272.79
Permanent Ineff=
       F       F
Bank Sta=253.75,300.16
XS Rating Curve= 0 ,0
Exp/Cntr(USF)=0,0
Exp/Cntr=0.3,0.1

Type RM Length L Ch R = 1 ,4998    ,199.6,221.4,237.9
XS GIS Cut Line= 4
2165514.18287707461343.7895785822165437.95900489461551.218476648
2165434.21028986461742.4029429382165310.50269403461866.110538773
#Sta/Elev= 30
       0 3277.76     2.6 3276.81      10 3278.15    18.5 3277.19      40 3265.38
    52.5 3261.73    65.4 3260.12   108.6  3260.1   133.5 3261.25   191.4 3261.76
     206  3262.9     231 3262.31     247 3263.95     283 3264.14     291  3263.4
     312  3258.3     319 3256.78   346.3 3256.71     359 3258.07     383 3264.17
     403 3264.75   452.4 3264.28   478.4 3260.92   489.2 3258.49     518 3258.58
   523.1 3259.98   528.8  3263.5   542.9 3274.67     574 3297.56   587.2 3303.87
#Mann= 4 ,-1,0
       0     .06       0     100      .1       0     312    .045       0
     359      .1       0
#XS Ineff= 2 , 0
          281.85    3267   393.4         3267.27
Permanent Ineff=
       F       F
Bank Sta=312,359
XS Rating Curve= 0 ,0
Exp/Cntr(USF)=0,0
Exp/Cntr=0.3,0.1

Type RM Length L Ch R = 1 ,4776    ,164,167,173
XS GIS Cut Line= 4
2165505.43587535461345.0391502572165357.98641768 461576.20991015
2165199.29081495461658.6816407072165171.80023809461677.425215833
#Sta/Elev= 30
       0 3276.49     4.9 3277.53    14.4 3276.36    24.2 3269.73    28.6 3267.44
    39.5 3263.44    52.4 3261.33    70.5 3260.29   158.5 3260.58   180.6 3261.31
   221.2 3259.93   241.4 3261.86   251.6 3261.14   265.9 3261.62   280.7 3260.57
   293.6  3255.5   307.8 3254.54   334.8 3258.36   348.4 3257.33   357.4 3257.48
   379.9 3255.03   411.5 3254.75   424.6 3253.74   433.5 3253.87   435.7 3254.95
     443 3258.45   448.3 3259.58   465.7 3261.22   478.8 3261.06   486.3 3261.78
#Mann= 4 ,-1,0
       0     .06       0     110      .1       0   411.5    .045       0
   435.7      .1       0
#XS Ineff= 2 , 0
          265.75 3262.94
Permanent Ineff=
       F       F
Bank Sta=411.5,435.7
XS Rating Curve= 0 ,0
Exp/Cntr(USF)=0,0
Exp/Cntr=0.3,0.1

Type RM Length L Ch R = 1 ,4609    ,201.8,188.8,158.3
XS GIS Cut Line= 4
2165494.18973027461342.5400069072165347.98984428461482.492034518
2165160.55409302461519.9791847712165120.56779942461613.697060403
#Sta/Elev= 30
       0 3275.54    11.8 3275.45    15.4 3274.27    23.1 3269.29    32.7 3264.52
    41.6 3262.22    85.8 3261.25   113.5 3257.89   144.7 3260.44   171.6    3259
   183.1 3259.75   200.5  3258.8   211.3 3259.77     243  3257.3   255.2 3251.33
   259.3 3250.51   275.2 3249.22   287.9 3250.49   300.1 3250.95   326.2 3255.02
   332.7 3254.72   340.9 3251.63   349.1 3254.25   361.3 3255.33   381.7 3253.18
   393.5 3255.11   416.1 3255.22   440.5 3258.99   452.7 3261.97   495.4 3263.91
#Mann= 4 ,-1,0
       0     .06       0     130      .1       0   259.3    .045       0
   287.9      .1       0
#XS Ineff= 2 , 0
                          362.49         3258.68
Permanent Ineff=
       F       F
Bank Sta=259.3,287.9
XS Rating Curve= 0 ,0
Exp/Cntr(USF)=0,0
Exp/Cntr=0.3,0.1

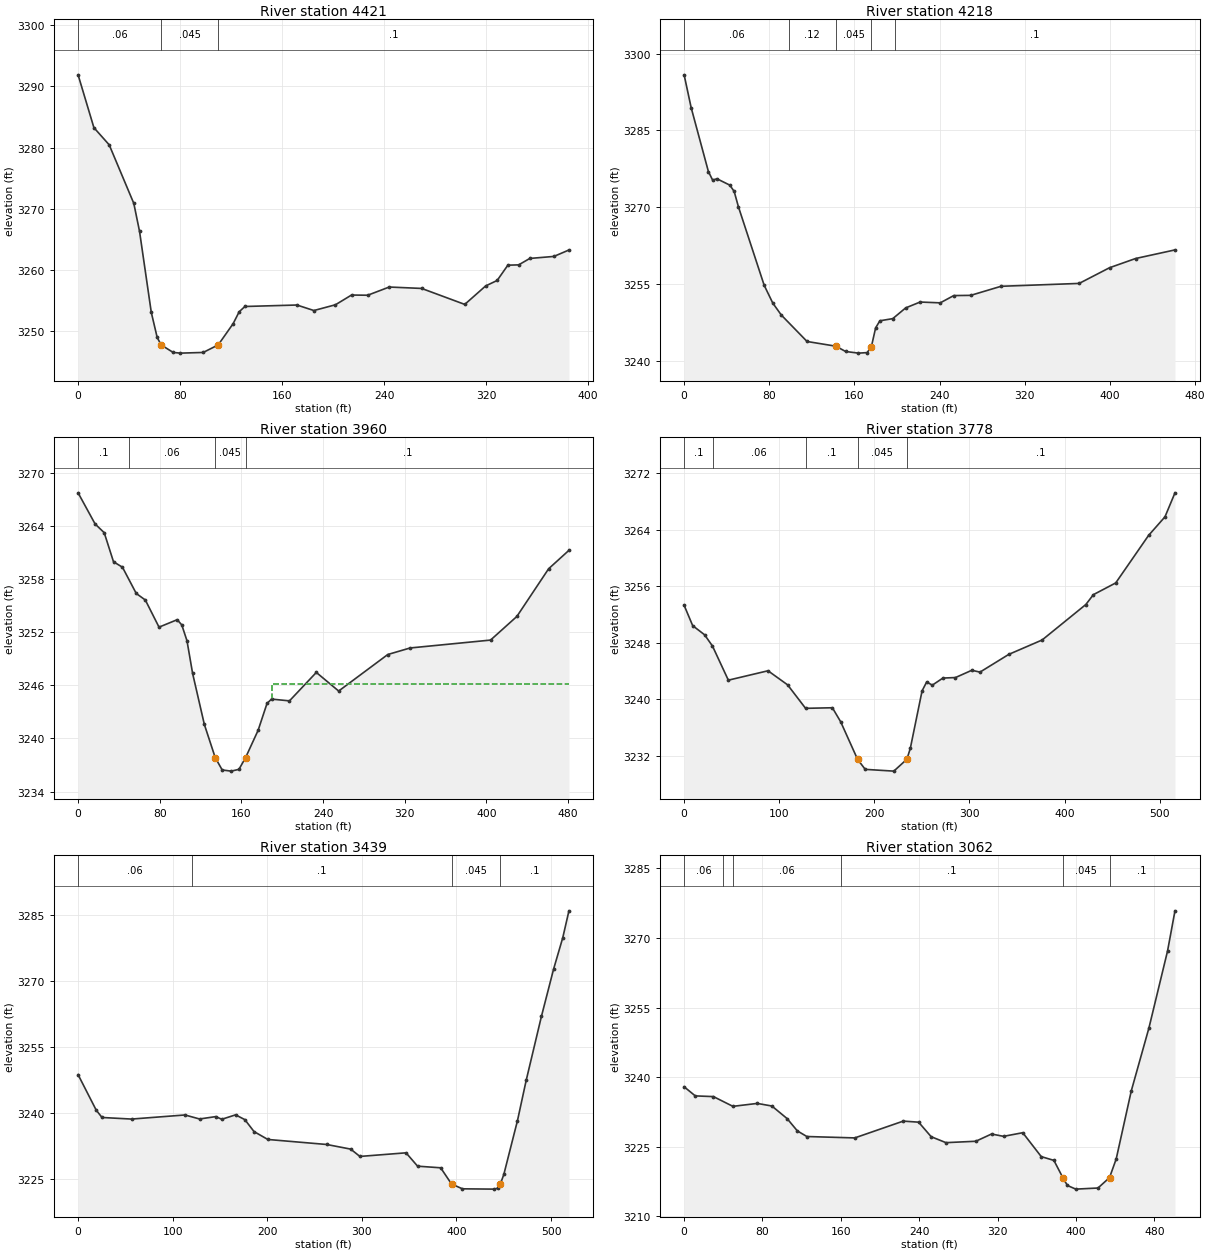
Type RM Length L Ch R = 1 ,4421    ,207.3,202.4,185.4
XS GIS Cut Line= 4
 2165261.7693987 461250.071702952165240.52668023461292.557139903
2165179.29766815461401.2698756372165110.57122601461602.450915327
#Sta/Elev= 30
       0 3291.88    12.4 3283.25    24.4 3280.44    43.7 3270.87    48.2 3266.29
    57.4 3253.07      62 3248.99    65.1 3247.75    74.6 3246.52    80.3 3246.41
    98.1 3246.52  109.863247.751   121.6 3251.23   126.3 3253.16   130.8 3254.03
   171.6 3254.27   184.9 3253.37   201.8 3254.31   214.4  3255.9   227.1 3255.87
     244 3257.21   269.4 3256.98   303.2 3254.37   319.6 3257.39   328.6 3258.28
     337 3260.78   345.5 3260.83   354.2 3261.88   373.1 3262.21   384.9 3263.26
#Mann= 3 ,-1,0
       0     .06       0    65.1    .045       0  109.86      .1       0
Bank Sta=65.1,109.86
XS Rating Curve= 0 ,0
Exp/Cntr(USF)=0,0
Exp/Cntr=0.3,0.1

Type RM Length L Ch R = 1 ,4218    ,267,258.5,244.5
XS GIS Cut Line= 4
2165046.84307059461142.6085388922165035.59692551461230.078556149
2165020.60206541461357.5348670082165068.08578906461597.452628627
#Sta/Elev= 30
       0 3295.86     6.6 3289.47    22.8 3276.99    26.8 3275.31    30.8 3275.58
    42.9 3274.34      47 3273.12      51 3270.12    75.2  3254.8    83.3 3251.32
    91.3 3248.99   115.5 3243.83   142.6 3242.91   151.7 3241.88   163.8 3241.56
   171.9 3241.66   175.9  3242.8   179.9 3246.49   183.9 3247.87     196 3248.29
   208.1 3250.38   221.7 3251.53   240.6 3251.37   253.3 3252.79   269.2 3252.83
   297.7  3254.6   371.1 3255.16   399.6 3258.22   424.1 3260.02   461.1  3261.7
#Mann= 5 ,-1,0
       0     .06       0   98.19     .12       0   142.6    .045       0
   175.9     .12       0  198.19      .1       0
Bank Sta=142.6,175.9
XS Rating Curve= 0 ,0
Exp/Cntr(USF)=0,0
Exp/Cntr=0.3,0.1

Type RM Length L Ch R = 1 ,3960    ,178.2,181.7,183
XS GIS Cut Line= 4
2164716.95614836461190.0922625452164765.68944369461288.808424878
2164813.17316734461393.7724455862164916.88761638461627.442348829
#Sta/Elev= 30
       0 3267.72    16.7  3264.2    25.6 3263.22    34.7 3259.94    43.5 3259.32
      57 3256.36    65.9 3255.62    79.3 3252.56    97.1  3253.4   101.6 3252.81
   106.7 3251.02   112.2 3247.34   123.7 3241.58  134.343237.842   141.2 3236.44
     150 3236.31   157.6 3236.51  164.123237.841   176.4 3240.92   185.1 3243.95
   189.5 3244.44   207.1 3244.24   233.4 3247.45   255.3 3245.35   303.4 3249.47
   325.3 3250.21   404.1  3251.1   429.9 3253.77     461 3259.15   480.9 3261.23
#Mann= 4 ,-1,0
       0      .1       0      50     .06       0  134.34    .045       0
  164.12      .1       0
#XS Ineff= 2 , 0
                          190.32         3246.14
Permanent Ineff=
       F       F
Bank Sta=134.34,164.12
XS Rating Curve= 0 ,0
Exp/Cntr(USF)=0,0
Exp/Cntr=0.3,0.1

Type RM Length L Ch R = 1 ,3778    ,322.6,339.3,355.7
XS GIS Cut Line= 4
2164630.73570278461212.584552697 2164594.4981242461335.042576857
2164653.22799293461481.2424628432164740.69801019461694.919219284
#Sta/Elev= 30
       0 3253.29       9 3250.41    21.5 3249.12    29.8 3247.53    46.5  3242.7
    88.2 3244.03   108.8 3242.04   127.7 3238.72   155.9  3238.8   164.6 3236.82
  182.32 3231.52   190.4 3230.09   220.5 3229.84   234.23231.518   237.8 3233.04
   250.2 3241.19     255 3242.44     261    3242   272.1    3243   285.3 3243.07
   302.5  3244.1   311.1 3243.84   341.4 3246.35   376.4 3248.38   422.4  3253.4
   430.3 3254.79   453.8 3256.45   488.3 3263.16   505.6  3265.8   516.1 3269.19
#Mann= 5 ,-1,0
       0      .1       0      30     .06       0  127.71      .1       0
  182.32    .045       0   234.2      .1       0
Bank Sta=182.32,234.2
XS Rating Curve= 0 ,0
Exp/Cntr(USF)=0,0
Exp/Cntr=0.3,0.1

Type RM Length L Ch R = 1 ,3439    ,357.2,377.1,398.3
XS GIS Cut Line= 4
2164502.02982024461136.3606805162164332.08807243461381.276728835
 2164303.3479239461546.220189948 2164288.3530638461597.452628627
#Sta/Elev= 30
       0 3248.75    19.2 3240.68    25.3 3239.03    56.5 3238.67     113  3239.6
   128.4 3238.69   145.6 3239.23   151.9 3238.62   166.5 3239.63   176.3 3238.54
     186 3235.83   200.6 3234.04   262.9  3232.9   288.2 3231.85   297.9 3230.19
   346.7 3231.01   358.9 3227.98   383.3 3227.61  394.813223.927   406.3 3222.84
   440.1 3222.77   444.2 3223.02  446.423223.925   450.1 3226.13   464.5 3238.32
   473.7 3247.45   489.8 3261.96   502.7 3272.72   512.4 3279.85   518.9 3285.93
#Mann= 4 ,-1,0
       0     .06       0     120      .1       0  394.81    .045       0
  446.42      .1       0
Bank Sta=394.81,446.42
XS Rating Curve= 0 ,0
Exp/Cntr(USF)=0,0
Exp/Cntr=0.3,0.1

Type RM Length L Ch R = 1 ,3062    ,202.5,205.4,203.1
XS GIS Cut Line= 4
2164347.08293253461010.1539413322164115.91217264461190.092262545
2163989.70543345461300.0545699542163958.46614158461326.295575131
#Sta/Elev= 30
       0 3237.93    11.4 3235.97    29.9 3235.82    49.8 3233.72    74.7 3234.35
    89.6 3233.79   105.1 3231.09   115.6 3228.43   125.3 3227.22   174.2 3226.92
   223.7 3230.54   239.4 3230.31   252.2 3227.18   267.3  3225.9   297.8  3226.2
   313.8 3227.76   326.1 3227.26   345.7 3228.04   364.6 3222.89   377.5 3222.08
   386.63218.369   391.3 3216.68   399.8 3215.89   422.5 3216.13  434.273218.366
   441.1 3222.39   456.5 3237.05   474.5 3250.59   493.5 3267.16   501.1 3275.83
#Mann= 6 ,-1,0
       0     .06       0      40      .1       0      50     .06       0
     160      .1       0   386.6    .045       0  434.27      .1       0
Bank Sta=386.6,434.27
XS Rating Curve= 0 ,0
Exp/Cntr(USF)=0,0
Exp/Cntr=0.3,0.1

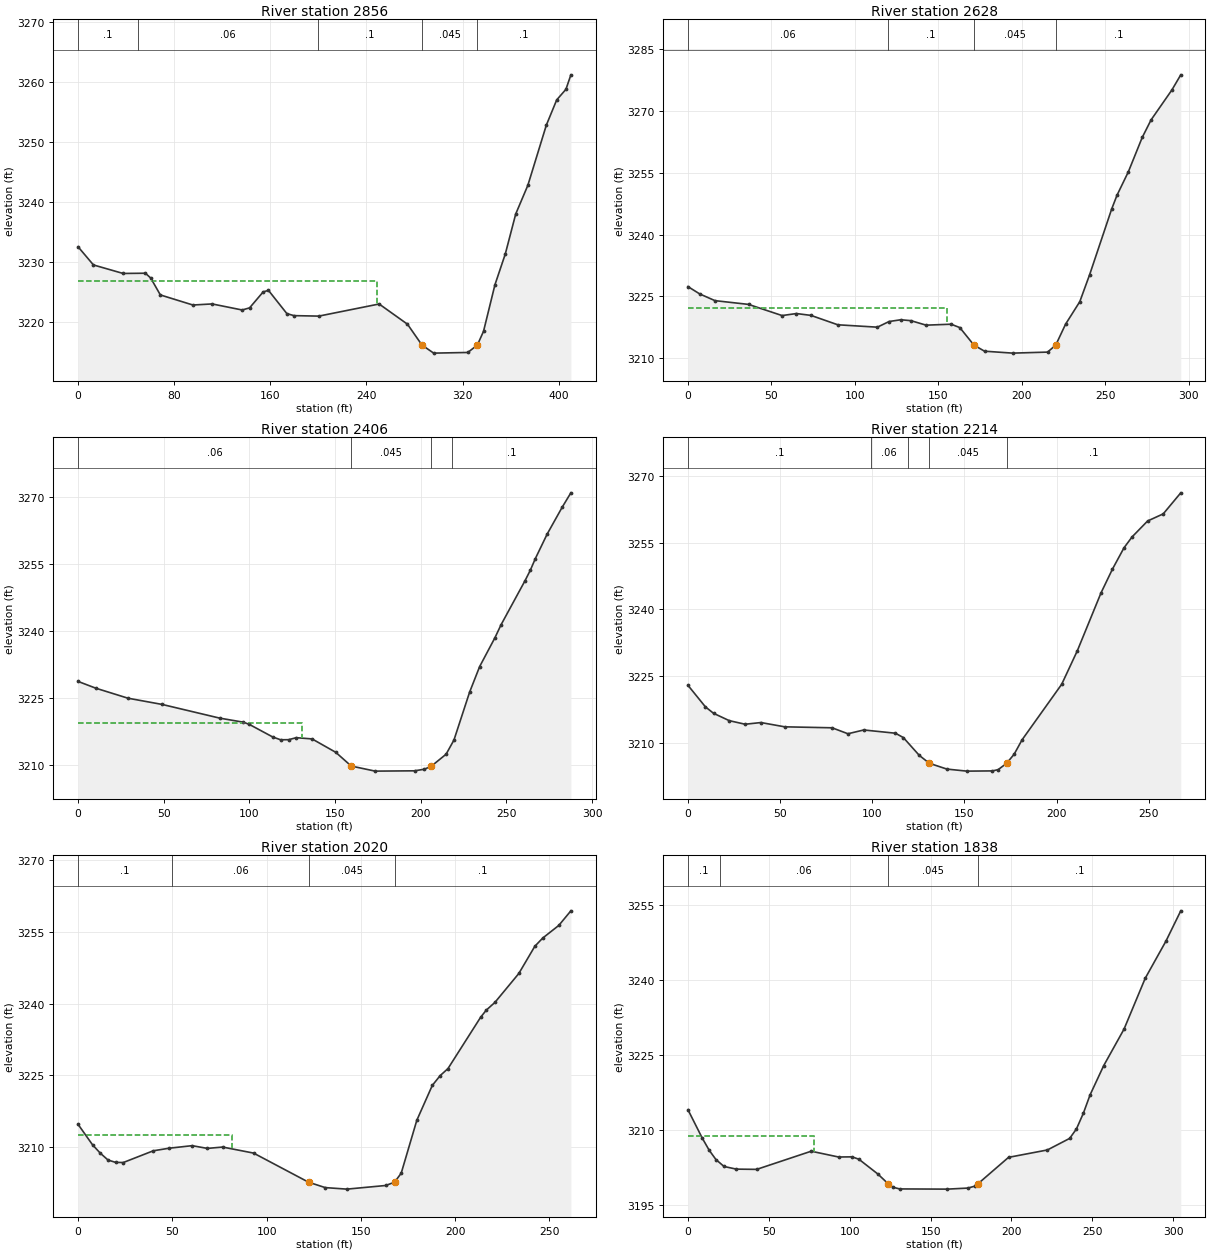
Type RM Length L Ch R = 1 ,2856    ,224.5,228.1,231.4
XS GIS Cut Line= 4
2164137.15489112460908.9386356492163974.71057335461046.391519909
2163849.75340584461153.8546839682163822.26282899461171.348687419
#Sta/Elev= 30
       0 3232.55    12.8 3229.52    37.5  3228.1    56.1 3228.14    60.5 3227.33
    68.5 3224.52    95.6 3222.84   111.6 3223.02   136.6 3222.01   142.8 3222.37
   154.1 3225.03   158.5 3225.28   173.8 3221.41   179.7 3221.07   200.4 3220.99
   250.6 3223.01   274.2 3219.64  286.253216.167     296 3214.82   324.4 3214.93
  332.373216.167   337.5 3218.46     347 3226.22   355.6 3231.34   364.3 3238.02
   374.4  3242.8   389.8 3252.84   398.4 3257.03   406.1  3258.8   410.2 3261.21
#Mann= 5 ,-1,0
       0      .1       0      50     .06       0     200      .1       0
  286.25    .045       0  332.37      .1       0
#XS Ineff= 2 , 0
          249.17 3226.91
Permanent Ineff=
       F       F
Bank Sta=286.25,332.37
XS Rating Curve= 0 ,0
Exp/Cntr(USF)=0,0
Exp/Cntr=0.3,0.1

Type RM Length L Ch R = 1 ,2628    ,219.7,222.5,224.2
XS GIS Cut Line= 4
2163925.97727802460816.4703316922163819.76368564460890.195060522
2163721.04752331460956.4223593022163681.06122971460981.413792804
#Sta/Elev= 30
       0 3227.39     7.1  3225.6    16.2 3223.98    36.3 3223.07    56.4 3220.36
      65 3220.85    73.7  3220.4    89.8 3218.12   113.5 3217.54   120.5 3218.91
   127.5 3219.34   133.6 3219.12   142.7 3218.03   157.7 3218.26   162.9 3217.44
  171.363213.191   177.7 3211.71   194.6 3211.24   215.5 3211.49  220.383213.191
   226.3 3218.29   234.8 3223.74   240.7  3230.3   253.9 3246.23   257.1 3249.58
   263.9 3255.27   272.2  3263.6   277.5 3267.86     290 3275.14   295.3  3278.8
#Mann= 4 ,-1,0
       0     .06       0     120      .1       0  171.36    .045       0
  220.38      .1       0
#XS Ineff= 2 , 0
          155.45 3222.09
Permanent Ineff=
       F       F
Bank Sta=171.36,220.38
XS Rating Curve= 0 ,0
Exp/Cntr(USF)=0,0
Exp/Cntr=0.3,0.1

Type RM Length L Ch R = 1 ,2406    ,187.7,191.8,195.6
XS GIS Cut Line= 4
2163814.76539894460644.0294405282163712.30052158460702.759309258
2163588.59292575460772.7353230632163563.60149225460783.981468139
#Sta/Elev= 30
       0 3228.78    10.4 3227.26    29.1 3225.03    49.1 3223.63    82.7 3220.57
    96.5 3219.66    99.8  3219.2   113.6 3216.36   118.2 3215.73   122.9 3215.75
   127.4  3216.2   136.6 3215.92   150.4 3212.93  159.443209.856   173.4 3208.72
   196.4 3208.79   202.2 3209.15  206.283209.854   214.8  3212.5   219.4 3215.68
   228.5 3226.35   234.4 3232.11   243.3 3238.54   246.9 3241.46   260.9 3251.32
   263.9 3253.59   266.9 3256.25   273.8 3261.73   282.6 3267.76287.6354 3270.95
#Mann= 4 ,-1,0
       0     .06       0  159.44    .045       0  206.28     .06       0
   218.1      .1       0
#XS Ineff= 2 , 0
          130.69 3219.52
Permanent Ineff=
       F       F
Bank Sta=159.44,206.28
XS Rating Curve= 0 ,0
Exp/Cntr(USF)=0,0
Exp/Cntr=0.3,0.1

Type RM Length L Ch R = 1 ,2214    ,189.9,194.2,196.3
XS GIS Cut Line= 4
2163721.04752331460504.0774129182163647.32279448460532.817561445
2163519.86648362460582.8004284492163471.13318829460599.044860225
#Sta/Elev= 30
       0 3222.92     9.5 3218.06    13.9 3216.62    22.4 3214.97      31 3214.16
    39.6 3214.54    52.5 3213.58    78.2 3213.36    86.8 3212.02    95.4 3212.87
   112.6 3212.14   116.9 3211.15   125.5 3207.16  130.983205.374   140.5 3204.07
   151.3 3203.61   165.2 3203.66   168.3 3203.94  172.933205.375     177 3207.42
   181.3 3210.66   202.8 3223.16   211.3 3230.72   224.1 3243.69   230.3 3249.04
   236.6 3253.86     241 3256.32   249.4 3259.89   257.9  3261.5267.4045 3266.23
#Mann= 5 ,-1,0
       0      .1       0   99.13     .06       0  119.13      .1       0
  130.98    .045       0  172.93      .1       0
Bank Sta=130.98,172.93
XS Rating Curve= 0 ,0
Exp/Cntr(USF)=0,0
Exp/Cntr=0.3,0.1

Type RM Length L Ch R = 1 ,2020    ,184.8,181.7,180
XS GIS Cut Line= 4
2163679.81165803 460342.882666832163597.33992747460356.627955256
2163468.63404494460389.1168188092163426.14860799 460404.11167891
#Sta/Elev= 30
       0 3214.79     7.7  3210.5    11.8 3208.76    15.9 3207.33    19.9 3206.84
      24 3206.81    39.9 3209.26    48.3  3209.8    60.5 3210.33    68.6 3209.76
    76.7 3210.04    93.1 3208.78  122.24  3202.7   131.1 3201.57   142.6 3201.25
   163.2 3202.01  167.883202.703   171.4 3204.57   179.7 3215.65   187.9 3222.92
   192.1 3224.98   196.2 3226.43   213.5 3237.14   216.5 3238.64   221.1 3240.26
   233.8 3246.31   242.3    3252   246.5 3253.72     255 3256.35261.4064  3259.4
#Mann= 4 ,-1,0
       0      .1       0      50     .06       0  122.24    .045       0
  167.88      .1       0
#XS Ineff= 2 , 0
           81.85 3212.55
Permanent Ineff=
       F       F
Bank Sta=122.24,167.88
XS Rating Curve= 0 ,0
Exp/Cntr(USF)=0,0
Exp/Cntr=0.3,0.1

Type RM Length L Ch R = 1 ,1838    ,153.3,155.2,156.3
XS GIS Cut Line= 4
2163648.57236615460145.4503421652163549.85620382460177.939205717
2163414.90246291460221.6742143462163358.67173753460239.168217797
#Sta/Elev= 30
       0 3214.04     8.8 3208.37    13.1 3205.93    17.3 3204.05    22.3 3202.66
    29.9 3202.13    42.5 3202.08    76.2 3205.72    93.1 3204.56   101.5 3204.59
   105.7 3204.11   117.4 3201.15   123.8 3199.19   126.7  3198.5   130.9 3198.16
   160.4 3198.12     173 3198.33   177.2  3198.7  179.28 3199.19   198.2 3204.49
   222.2 3205.97     236 3208.29   240.2  3210.2   244.5 3213.37   248.6 3217.01
     257 3222.86   269.6  3230.2   282.7 3240.39   295.5 3247.83304.6777 3253.91
#Mann= 4 ,-1,0
       0      .1       0      20     .06       0   123.8    .045       0
  179.28      .1       0
#XS Ineff= 2 , 0
           77.78 3208.77
Permanent Ineff=
       F       F
Bank Sta=123.8,179.28
XS Rating Curve= 0 ,0
Exp/Cntr(USF)=0,0
Exp/Cntr=0.3,0.1

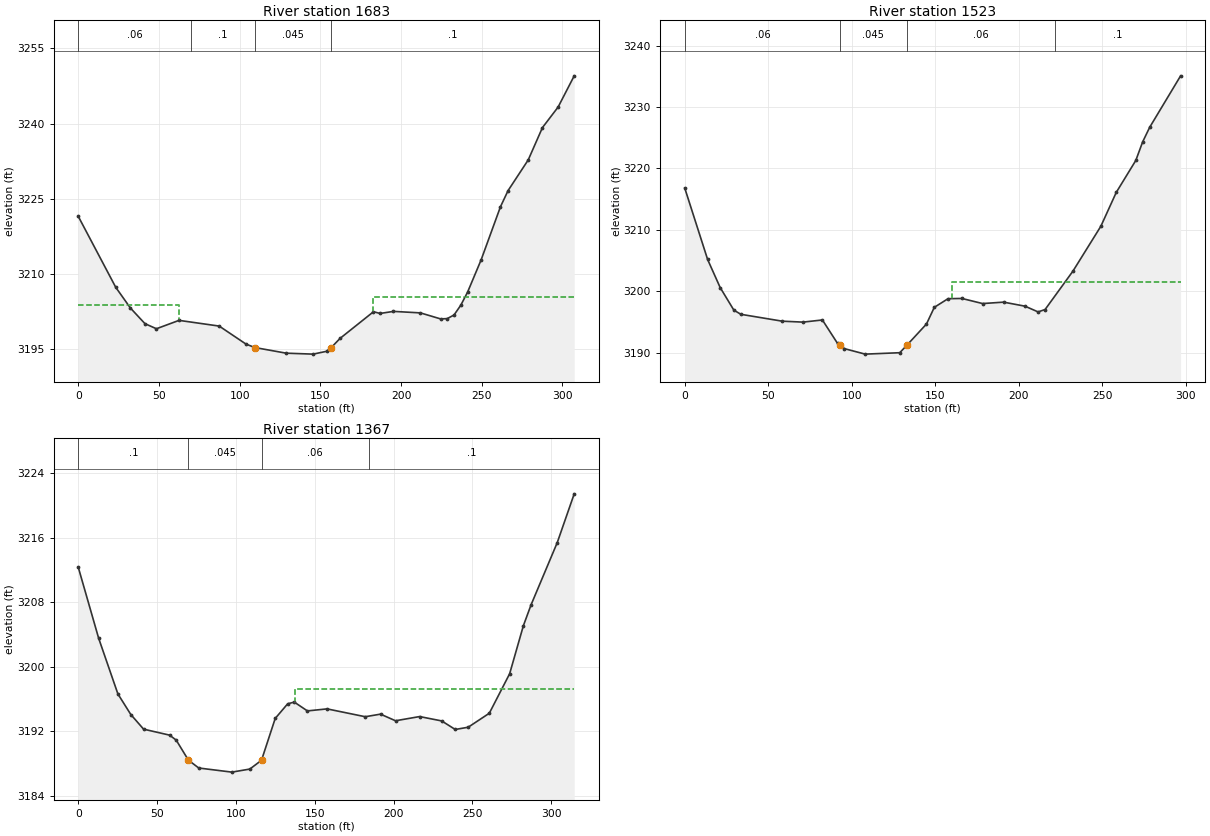
Type RM Length L Ch R = 1 ,1683    ,158.5,159.3,160
XS GIS Cut Line= 4
 2163596.0903558459994.2521694782163528.61348534460025.491461356
2163391.16060108460064.228183284 2163304.9401555460090.469188461
#Sta/Elev= 30
       0  3221.5    23.2 3207.37    32.3 3203.24    41.3 3200.13    48.4 3199.12
    62.4 3200.79    87.3 3199.65   103.9 3196.06  109.44 3195.37   128.8 3194.25
   145.5 3194.06   153.8 3194.62  156.72 3195.37   162.2  3197.2   182.9 3202.51
     187 3202.17   195.3 3202.58     212 3202.28   224.5 3201.08   228.6 3201.14
   232.8 3201.86     237 3203.81   241.2 3206.41   249.6 3212.85   261.6 3223.45
   266.3 3226.66   278.8 3232.78   287.6 3239.22   297.3 3243.31307.2896 3249.54
#Mann= 4 ,-1,0
       0     .06       0      70      .1       0  109.44    .045       0
  156.72      .1       0
#XS Ineff= 2 , 0
           62.54 3203.79  182.89         3205.45
Permanent Ineff=
       F       F
Bank Sta=109.44,156.72
XS Rating Curve= 0 ,0
Exp/Cntr(USF)=0,0
Exp/Cntr=0.3,0.1

Type RM Length L Ch R = 1 ,1523    ,156.8,156.8,154.9
XS GIS Cut Line= 4
2163548.60663215459856.7992852182163497.37419347459870.544573644
2163353.67345083459908.0317238972163262.45471855459935.522300749
#Sta/Elev= 30
       0 3216.82    13.7 3205.19    21.2 3200.63    29.4 3196.95    33.6 3196.27
    58.4 3195.15    70.8    3195    82.4 3195.35    91.5 3191.52   93.053191.198
    95.6 3190.68     108 3189.79   128.7 3190.02  132.823191.197   144.7 3194.69
   149.4 3197.41   157.6 3198.81   165.9 3198.85   178.3 3198.02   190.9 3198.25
   203.7 3197.59   211.5 3196.66   215.7 3197.05   232.4 3203.31   249.1 3210.61
   258.3 3216.11     270 3221.31   274.1 3224.33   278.3  3226.7296.8253 3235.08
#Mann= 4 ,-1,0
       0     .06       0   93.05    .045       0  132.82     .06       0
  221.55      .1       0
#XS Ineff= 2 , 0
                          159.74         3201.45
Permanent Ineff=
       F       F
Bank Sta=93.05,132.82
XS Rating Curve= 0 ,0
Exp/Cntr(USF)=0,0
Exp/Cntr=0.3,0.1

Type RM Length L Ch R = 1 ,1367    ,198.1,188.8,181.2
XS GIS Cut Line= 4
2163504.87162352459710.5993992312163458.63747154459719.346400957
2163336.17944738 459754.334407862163206.22399317459806.816418214
#Sta/Elev= 30
       0 3212.29    12.9 3203.52    25.1 3196.63    33.3 3194.08    41.4 3192.27
    57.9 3191.53    62.1 3190.91   69.843188.429    76.4 3187.46    97.4 3186.95
   108.8 3187.33   116.2 3188.42   124.9  3193.6   132.8 3195.41     137 3195.62
   145.3 3194.53   157.8 3194.78     182 3193.81   191.7 3194.13   201.2 3193.31
   216.5 3193.83   230.5 3193.29   239.1 3192.23   247.3 3192.51   260.7 3194.24
   273.6 3199.13   282.3 3205.07   287.2 3207.67   303.8 3215.37314.5653 3221.41
#Mann= 4 ,-1,0
       0      .1       0   69.84    .045       0   116.2     .06       0
  184.41      .1       0
#XS Ineff= 2 , 0
                          137.46          3197.3
Permanent Ineff=
       F       F
Bank Sta=69.84,116.2
XS Rating Curve= 0 ,0
Exp/Cntr(USF)=0,0
Exp/Cntr=0.3,0.1