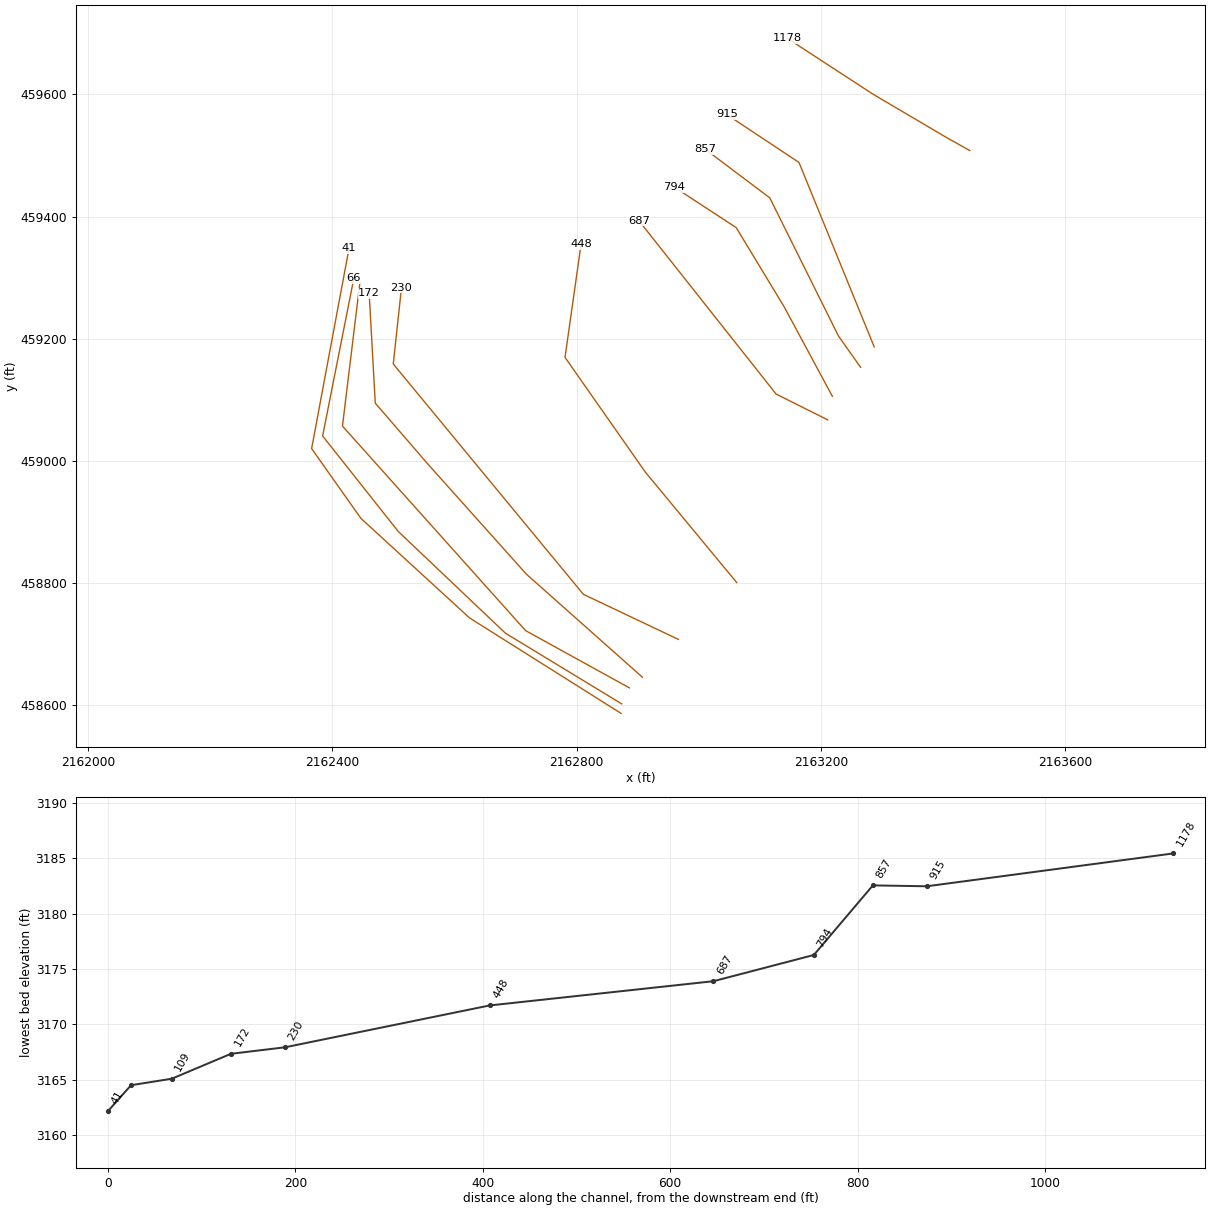
HEC-RAS study NFCRNBRYRV.prj: NFCRNBRYRV

--- NFCRNBRYRV.g01 (geometry) --- (continued)

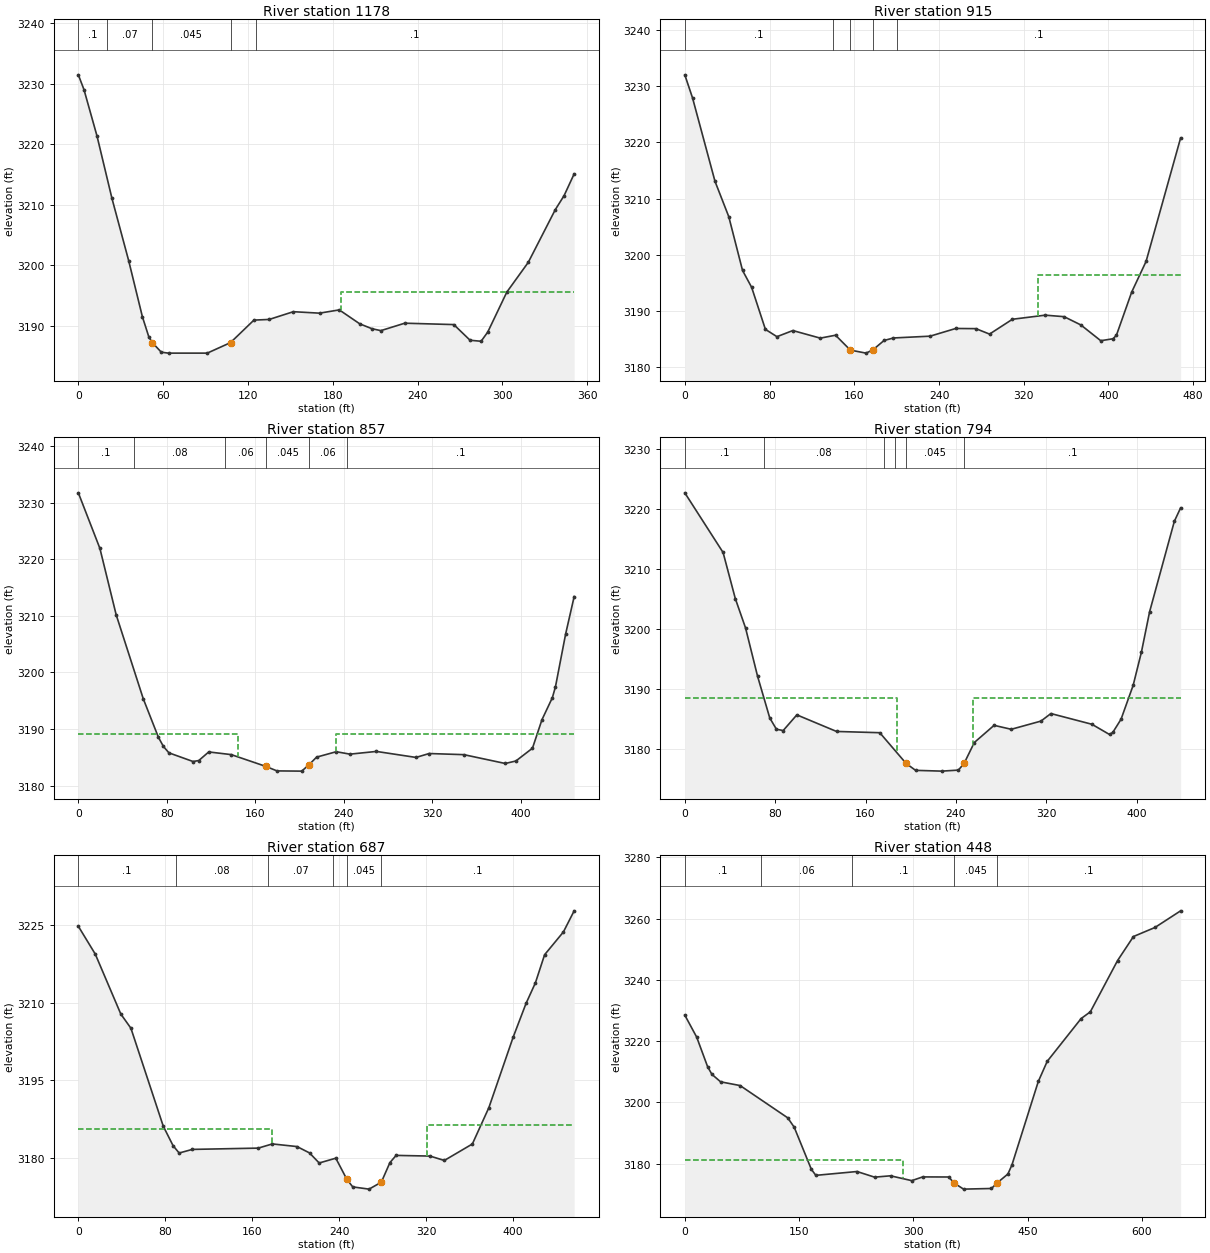
Type RM Length L Ch R = 1 ,1178    ,277.1,263.2,249.1
XS GIS Cut Line= 4
2163443.64261144459508.1687878662163403.65631783459530.661078018
 2163284.9470087459600.6370918232163144.99498109459691.855824105
#Sta/Elev= 30
       0 3231.46       4 3229.01    13.2 3221.35    23.8 3211.01    35.6 3200.74
    45.3 3191.47    49.9  3188.1   52.353187.177    58.7 3185.59    63.8 3185.44
    91.2 3185.44  107.653187.178   124.2  3190.9     135 3191.01   152.1 3192.29
   170.6 3192.05   184.6 3192.59   199.1 3190.28   207.8 3189.47     214 3189.16
   230.9 3190.39   265.6 3190.16   277.1 3187.57   284.9  3187.4   289.6 3188.92
   303.1 3195.53   318.3 3200.46   337.4 3209.17   343.6 3211.48350.7323 3215.08
#Mann= 5 ,-1,0
       0      .1       0      20     .07       0   52.35    .045       0
  107.65     .06       0  125.88      .1       0
#XS Ineff= 2 , 0
                          186.03         3195.59
Permanent Ineff=
       F       F
Bank Sta=52.35,107.65
XS Rating Curve= 0 ,0
Exp/Cntr(USF)=0,0
Exp/Cntr=0.3,0.1

Type RM Length L Ch R = 1 ,915     ,55.1,57.5,58.8
XS GIS Cut Line= 3
2163287.21995718459186.7637235762163164.04226023459488.669843548
 2163045.6950612459567.165434741
#Sta/Elev= 30
       0 3232.03     7.3 3227.92    28.5 3213.07    41.5 3206.78    54.5  3197.2
    63.1 3194.19    76.1  3186.7      87  3185.4     102 3186.49   127.9 3185.14
   142.3 3185.66   156.3 3183.01   171.1 3182.47   177.5 3183.04   188.1 3184.72
     197 3185.17   231.6 3185.49   255.8 3186.86   274.8 3186.83   287.7 3185.86
   309.3  3188.5   340.3 3189.23   358.1 3188.96   373.9 3187.49   392.7 3184.68
   404.3 3185.03   407.5 3185.66   421.9 3193.34   435.5 3198.81   468.1  3220.8
#Mann= 5 ,-1,0
       0      .1       0     140     .06       0   156.3    .045       0
   177.5     .06       0     200      .1       0
#XS Ineff= 2 , 0
                          333.33         3196.38
Permanent Ineff=
       F       F
Bank Sta=156.3,177.5
XS Rating Curve= 0 ,0
Exp/Cntr(USF)=0,0
Exp/Cntr=0.5,0.3

Type RM Length L Ch R = 1 ,857     ,60.6,63,67.7
XS GIS Cut Line= 4
 2163264.9538619459153.2904321392163228.71628332459204.522870818
2163116.25483256 459430.695344012163010.04124018459510.667931216
#Sta/Elev= 30
       0 3231.72    19.5  3221.9    34.2 3210.18    58.7 3195.34    72.4 3188.53
    76.9 3186.92    81.9 3185.78   103.7 3184.25   108.9 3184.42   117.9 3185.94
   138.2 3185.47   169.6 3183.38   179.6 3182.59     202 3182.55  208.773183.721
   215.4 3185.02   233.2 3185.98   245.6 3185.55   269.5 3186.03   305.3 3184.97
   317.2 3185.66   348.6 3185.46     386  3183.9   395.6 3184.34   410.6  3186.6
   419.2 3191.64   428.6 3195.53   431.4 3197.46   440.6 3206.79448.2973 3213.39
#Mann= 6 ,-1,0
       0      .1       0      50     .08       0  132.75     .06       0
   169.6    .045       0  208.77     .06       0  242.75      .1       0
#XS Ineff= 2 , 0
          144.66 3189.09  233.22         3189.18
Permanent Ineff=
       F       F
Bank Sta=169.6,208.77
XS Rating Curve= 0 ,0
Exp/Cntr(USF)=0,0
Exp/Cntr=0.5,0.3

Type RM Length L Ch R = 1 ,794     ,103.7,107.2,110.8
XS GIS Cut Line= 4
2163218.71970992459105.8067084852163139.99669439459252.006594471
2163061.27367886459381.9620486812162960.05837317459448.189347461
#Sta/Elev= 30
       0 3222.76    33.9 3212.79    44.7  3205.1    53.8 3200.17    64.4 3192.13
    75.2 3185.15    81.1 3183.26    87.1 3183.04    99.2 3185.66   134.3 3182.89
   172.6 3182.68  195.893177.553   204.3 3176.39   227.5 3176.26   242.2 3176.43
  247.273177.555   256.3 3181.04   273.8 3183.91     289 3183.25   315.3 3184.62
   324.1 3185.88   360.4 3184.09     376 3182.38   378.9 3182.73   386.2 3184.93
   396.9 3190.58   404.2 3196.11   411.5  3202.9   433.4 3218.01438.9442 3220.25
#Mann= 6 ,-1,0
       0      .1       0      70     .08       0  176.05     .07       0
  186.05      .1       0  195.89    .045       0  247.27      .1       0
#XS Ineff= 2 , 0
             188 3188.48     255         3188.48
Permanent Ineff=
       F       F
Bank Sta=195.89,247.27
XS Rating Curve= 0 ,0
Exp/Cntr(USF)=0,0
Exp/Cntr=0.5,0.3

Type RM Length L Ch R = 1 ,687     ,240.6,238.7,237.1
XS GIS Cut Line= 3
2163211.13961494459067.2089000672163126.60590135459109.475756863
2162901.98774809459393.267509637
#Sta/Elev= 30
       0 3224.78    15.6 3219.39    39.1 3207.79    48.4 3205.04    78.2 3186.06
    87.2 3182.31    92.8 3180.88   104.9 3181.58   165.6 3181.83   178.6 3182.64
   201.3 3182.13   212.8  3180.9   221.7 3178.95     237 3179.88   247.2 3175.77
   252.6 3174.32   267.6 3173.89   278.9 3175.23   286.8 3179.02   292.5 3180.42
   323.7 3180.29   336.9 3179.44   362.7 3182.63   377.9 3189.67   400.2 3203.28
   412.1 3209.84   420.7 3213.81   429.2 3219.27   446.5 3223.68   456.4 3227.77
#Mann= 6 ,-1,0
       0      .1       0      90     .08       0  174.51     .07       0
  234.51      .1       0   247.2    .045       0   278.9      .1       0
#XS Ineff= 2 , 0
          178.69 3185.48  321.31         3186.38
Permanent Ineff=
       F       F
Bank Sta=247.2,278.9
XS Rating Curve= 0 ,0
Exp/Cntr(USF)=0,0
Exp/Cntr=0.3,0.1

Type RM Length L Ch R = 1 ,448     ,215.8,218.2,220.2
XS GIS Cut Line= 4
2163062.09367101458800.917256552   2162912.14507458982.105149441
2162780.94004411459169.5409007052162807.18104929 459354.47750862
#Sta/Elev= 30
       0 3228.53    15.6 3221.34      30 3211.64    35.6 3209.18      47 3206.74
    72.6 3205.52   135.1 3194.98   143.6 3191.92   166.1 3178.17     172  3176.2
     226 3177.45   249.1 3175.61     270 3176.05   297.9 3174.47   312.2 3175.69
   346.4 3175.66   353.7 3173.65   365.9  3171.7   402.5 3171.91   409.8 3173.69
   424.1 3176.64   429.4 3179.61     464 3206.86   475.7 3213.43   520.2  3227.4
   532.3  3229.6     568 3246.33   588.9 3254.19   617.1 3257.14   650.8 3262.58
#Mann= 5 ,-1,0
       0      .1       0     100     .06       0     220      .1       0
   353.7    .045       0   409.8      .1       0
#XS Ineff= 2 , 0
          286.47 3181.27
Permanent Ineff=
       F       F
Bank Sta=353.7,409.8
XS Rating Curve= 0 ,0
Exp/Cntr(USF)=0,0
Exp/Cntr=0.3,0.1

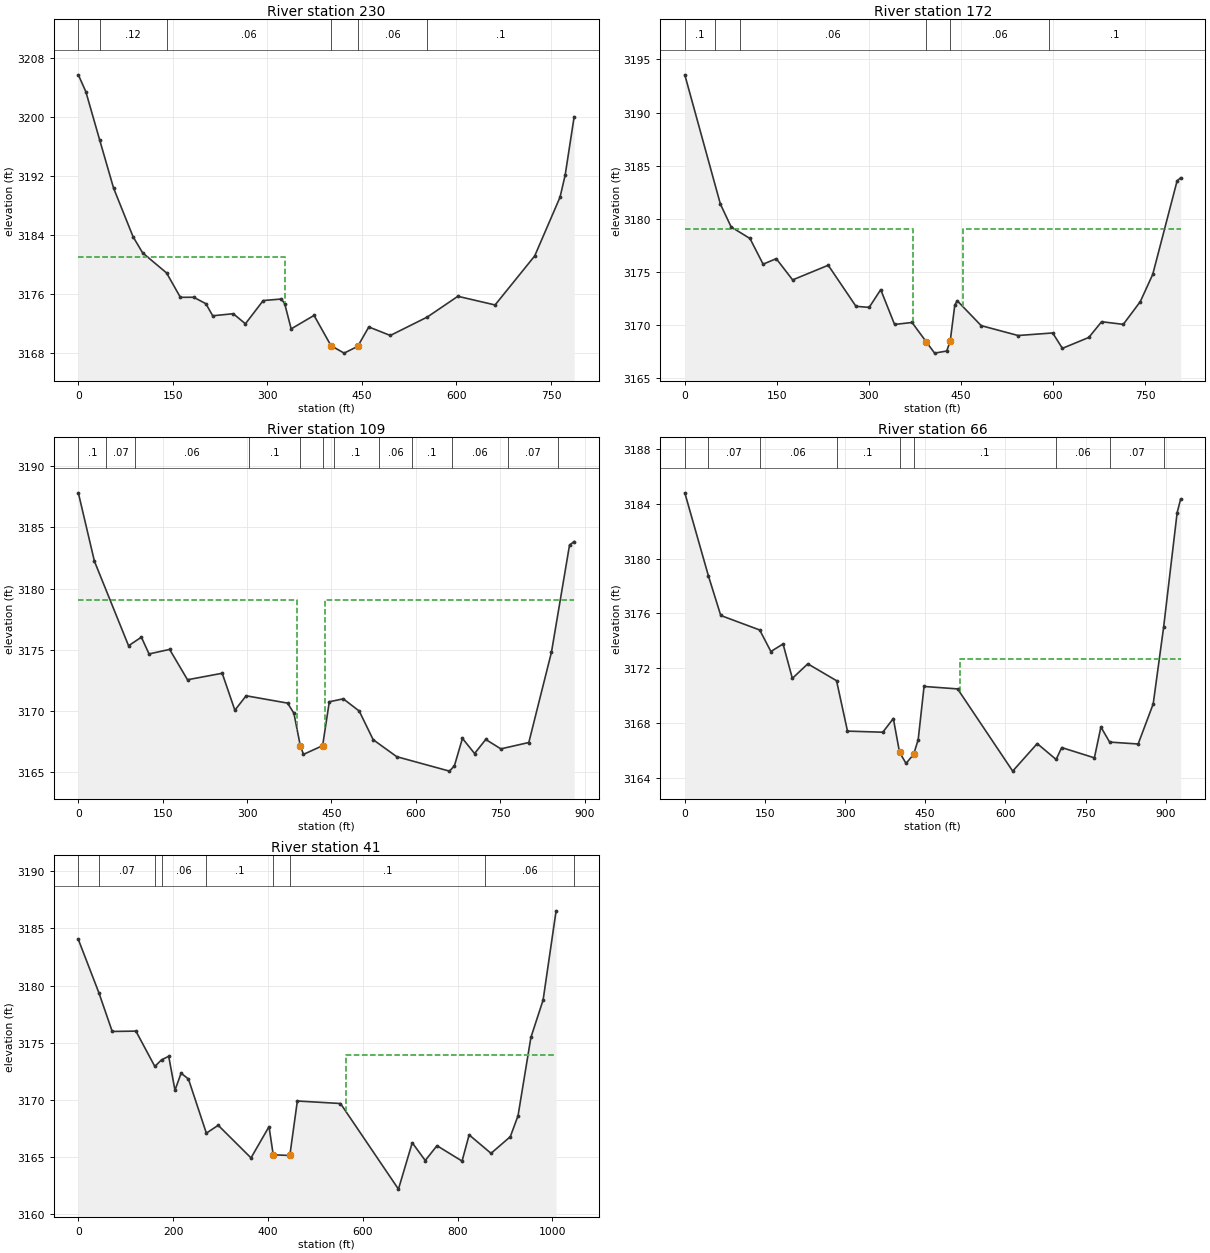
Type RM Length L Ch R = 1 ,230     ,56.5,57.8,58.8
XS GIS Cut Line= 4
2162966.64617949458707.8084843242162810.99680208458781.607758095
2162499.69804727459158.6549568162162513.11609704459283.442819738
#Sta/Elev= 30
       0 3205.77    11.9 3203.48    33.7 3196.96    55.9 3190.37    86.8 3183.76
     102 3181.56     140 3178.83   161.9 3175.51     183 3175.52   202.4 3174.64
   213.2    3173   245.8 3173.28   265.1 3171.91   293.3 3175.07   322.1 3175.28
   327.4 3174.65   337.7 3171.22     374 3173.05   400.93168.934   421.7 3167.92
   443.33168.845   460.9 3171.48     495 3170.32   553.7 3172.83   602.2 3175.65
   661.2 3174.47   724.1 3181.14   764.3 3189.13   772.4 3192.12   786.7 3200.07
#Mann= 6 ,-1,0
       0      .1       0    33.7     .12       0     140     .06       0
   400.9    .045       0   443.3     .06       0   553.7      .1       0
#XS Ineff= 2 , 0
          327.15    3181
Permanent Ineff=
       F       F
Bank Sta=400.9,443.3
XS Rating Curve= 0 ,0
Exp/Cntr(USF)=0,0
Exp/Cntr=0.5,0.3

Type RM Length L Ch R = 1 ,172     ,63,63.1,63
XS GIS Cut Line= 5
2162907.57636282458645.9643320492162717.64146821458814.656508187
2162557.69629379458993.3452577262162470.22627654459094.560563409
2162460.22970314459274.498884623
#Sta/Elev= 30
       0 3193.55      58 3181.37    75.5 3179.22   106.2 3178.13   127.6 3175.71
     149 3176.23   175.7 3174.23   233.7 3175.61   278.9 3171.74   300.4 3171.64
   319.2 3173.31   341.8 3170.03   370.2 3170.22  393.533168.385     407 3167.33
   426.8 3167.53   432.5 3168.49   439.9 3171.85   443.8 3172.27   482.9 3169.92
     543 3168.99   599.4 3169.23   615.2 3167.78   658.3 3168.81   679.1 3170.29
   714.4 3170.04   742.1 3172.18   762.4 3174.75   802.1 3183.56 807.839 3183.85
#Mann= 6 ,-1,0
       0      .1       0      50     .12       0      90     .06       0
  393.53    .045       0   432.5     .06       0  593.85      .1       0
#XS Ineff= 2 , 0
             372 3179.04     453         3179.04
Permanent Ineff=
       F       F
Bank Sta=393.53,432.5
XS Rating Curve= 0 ,0
Exp/Cntr(USF)=0,0
Exp/Cntr=0.5,0.3

Type RM Length L Ch R = 1 ,109     ,41.7,43.5,45.8
XS GIS Cut Line= 4
2162886.33364434458628.4703285982162716.39189653 458722.18820423
2162416.49469451459057.0734131562162445.23484304459293.242459749
#Sta/Elev= 30
       0 3187.83    28.6 3182.24    89.3 3175.33   112.1 3176.03   125.7 3174.66
   162.3 3175.03   194.1 3172.55   255.8 3173.08   278.3 3170.06   298.3 3171.24
     372 3170.64   383.3 3169.81   394.6 3167.16   400.3 3166.45   434.3 3167.16
   446.2 3170.75   471.1 3170.99   499.4 3169.99   524.2 3167.65   566.1 3166.26
   659.8 3165.08   668.6 3165.51   682.9 3167.76   704.5 3166.52   724.3 3167.67
   751.2  3166.9   800.9 3167.42   841.2 3174.81   873.3 3183.56881.5218 3183.85
#Mann= 12 ,-1,0
       0      .1       0      50     .07       0     100     .06       0
  304.07      .1       0   394.6    .045       0   434.3     .06       0
  454.07      .1       0  534.07     .06       0  594.07      .1       0
  663.61     .06       0  763.61     .07       0  853.61      .1       0
#XS Ineff= 2 , 0
             389 3179.04     439         3179.04
Permanent Ineff=
       F       F
Bank Sta=394.6,434.3
XS Rating Curve= 0 ,0
Exp/Cntr(USF)=0,0
Exp/Cntr=0.5,0.3

Type RM Length L Ch R = 1 ,66      ,24.5,24.7,25.2
XS GIS Cut Line= 5
2162873.83792759458602.2293234212162683.25811774458718.042618289
2162507.93991244458884.4200614392162384.00583096 459040.82898138
2162435.23826963459299.490318125
#Sta/Elev= 30
       0  3184.8    44.2 3178.74    67.3 3175.85   140.2 3174.79   161.1 3173.22
   183.9 3173.77   201.3 3171.26   230.2 3172.32     284 3171.09   304.5 3167.41
   370.6 3167.33   390.3 3168.33   401.9 3165.87   414.1 3165.05   428.3 3165.72
   436.8 3166.78   447.8 3170.67   510.6 3170.49   613.7 3164.49   659.6  3166.5
     695 3165.34   705.4 3166.21   766.6 3165.46   778.8 3167.71   795.1 3166.61
   848.5 3166.47   876.7  3169.4   896.2    3175   921.5 3183.36     928 3184.34
#Mann= 9 ,-1,0
       0      .1       0    44.2     .07       0   140.2     .06       0
     284      .1       0   401.9    .045       0   428.3      .1       0
     695     .06       0   795.1     .07       0   896.2      .1       0
#XS Ineff= 2 , 0
                          514.37         3172.69
Permanent Ineff=
       F       F
Bank Sta=401.9,428.3
XS Rating Curve= 0 ,0
Exp/Cntr(USF)=0,0
Exp/Cntr=0.3,0.1

Type RM Length L Ch R = 1 ,41      ,,,
XS GIS Cut Line= 5
 2162872.7007187 458586.694346892162624.55385447458743.015001113
 2162446.8437387458905.8091751532162365.99284814 459020.18862608
2162427.30341229459348.117480477
#Sta/Elev= 30
       0 3184.04    43.2 3179.38    71.5 3175.97   121.5    3176   161.4  3172.9
   175.5 3173.48   190.7 3173.79   203.9 3170.81   216.8 3172.31   232.3  3171.8
   270.1 3167.05   295.1 3167.74   364.3 3164.88   402.3 3167.62   411.2 3165.15
  446.213165.093   462.1 3169.87   553.1 3169.65   675.4 3162.14   704.5 3166.21
   731.9 3164.65   756.7 3165.95   809.6  3164.6   824.5  3166.9   870.7 3165.28
   911.4 3166.74   927.7 3168.58   954.8 3175.44   980.6 3178.73    1008 3186.55
#Mann= 9 ,-1,0
       0      .1       0    43.2     .07       0   161.4     .12       0
   175.5     .06       0   270.1      .1       0   411.2    .045       0
  446.21      .1       0     858     .06       0  1046.1      .1       0
#XS Ineff= 2 , 0
                          565.52         3173.91
Permanent Ineff=
       F       F
Bank Sta=411.2,446.21
XS Rating Curve= 0 ,0
Exp/Cntr(USF)=0,0
Exp/Cntr=0.3,0.1
LCMann Table=0

Chan Stop Cuts=-1
Use User Specified Reach Order=0
Composite Channel Slope=5